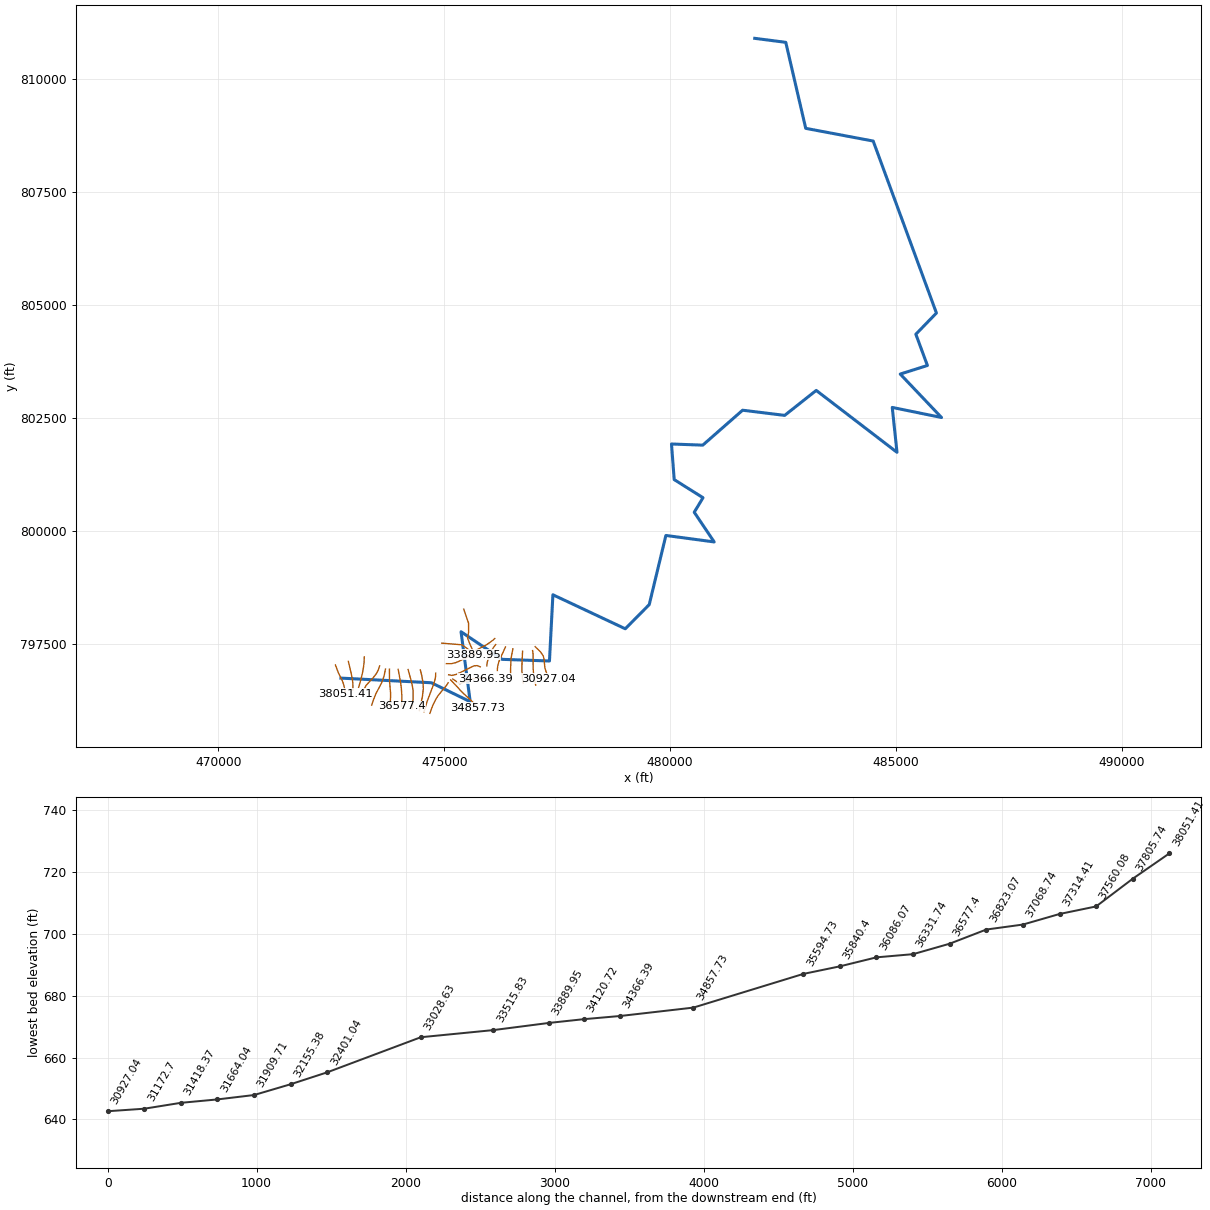
--- 5528_ras.prj (project) ---

Proj Title=5528
Current Plan=p01
Default Exp/Contr=0.3,0.1
English Units
Geom File=g01
Flow File=f01
Plan File=p01
Y Axis Title=Elevation
X Axis Title(PF)=Main Channel Distance
X Axis Title(XS)=Station
BEGIN DESCRIPTION:
RFD model 5528 exported to HEC-RAS
END DESCRIPTION:

--- 5528_ras.p01 (plan) ---

Plan Title=Plan 01
Program Version=4.10
Short Identifier=Plan 01
Geom File=g01
Flow File=f01
Subcritical Flow
Calc Critical at every XS
Secant Critical Depth

--- 5528_ras.f01 (steady flow) ---

Flow Title=Flow 01
Program Version=5.01
Number of Profiles= 6
Profile Names=10yr,25yr,50yr,100yr,100plus,500yr
River Rch & RM=5528,127,38051.41
11087.2117180.2322795.8727568.49   4025037045.55
River Rch & RM=5528,127,37805.74
 11092.917189.2622808.0327583.3940271.7537063.29
River Rch & RM=5528,127,37560.08
11107.9617213.1622840.2727622.8940329.4337110.36
River Rch & RM=5528,127,37314.41
 11117.717228.6322861.15 27648.540366.8137140.91
River Rch & RM=5528,127,37068.74
11124.5317239.4822875.7927666.44   40393 37162.3
River Rch & RM=5528,127,36823.07
11127.2617243.8222881.6427673.6140403.4737170.85
River Rch & RM=5528,127, 36577.4
11180.9417328.8722996.2127813.8740608.2537337.45
River Rch & RM=5528,127,36331.74
11197.8417355.8223032.6727858.6640673.6437391.09
River Rch & RM=5528,127,36086.07
11202.4217363.1323042.5627870.8340691.4137405.71
River Rch & RM=5528,127, 35840.4
11209.8817375.0423058.6827890.6440720.3437429.47
River Rch & RM=5528,127,35594.73
11212.1617378.6923063.6327896.7340729.2237436.78
River Rch & RM=5528,127,34857.73
11324.1417556.9223304.3928192.2141160.63 37789.4
River Rch & RM=5528,127,34366.39
11336.1317576.1523330.5128224.4141207.6437828.23
River Rch & RM=5528,127,34120.72
11339.8817582.1723338.6828234.4741222.3437840.36
River Rch & RM=5528,127,33889.95
11343.46 17587.923346.4628244.0641236.3337851.89
River Rch & RM=5528,127,33515.83
11349.3417597.31 23359.228259.7341259.2137870.68
River Rch & RM=5528,127,33028.63
11443.3917747.5623562.6728509.9741624.5538170.36
River Rch & RM=5528,127,32401.04
11485.55 17815.523655.1628624.2641791.4138308.68
River Rch & RM=5528,127,32155.38
11488.3317819.9823661.2428631.7641802.3838317.73
River Rch & RM=5528,127,31909.71
 11492.617826.8323670.5628643.2741819.1838331.61
River Rch & RM=5528,127,31664.04
11496.6817833.3923679.4828654.2741835.2438344.89
River Rch & RM=5528,127,31418.37
11514.7217862.3723718.8528702.8541906.16 38403.4
River Rch & RM=5528,127, 31172.7
11518.0517867.7323726.1428711.8441919.2938414.25
River Rch & RM=5528,127,30927.04
11526.0617880.6723743.7928733.6941951.1838440.78
River Rch & RM=5528,127,30681.37
11531.6817889.7823756.2128749.0741973.6438459.46
River Rch & RM=5528,127, 30435.7
11535.6817896.2423765.0328759.9841989.5738472.72
River Rch & RM=5528,127,30190.03
11539.1317901.8123772.64 28769.442003.3338484.17
River Rch & RM=5528,127,29487.51
11557.3417931.2423812.7728819.0642075.83 38544.4
River Rch & RM=5528,127,28743.81
11607.3318012.2923923.5328956.3842276.3138711.66
River Rch & RM=5528,127,28224.69
11619.5418032.0923950.5928989.93 42325.338752.52
River Rch & RM=5528,127,27979.02
11625.9718042.5423964.8829007.6642351.1938774.16
River Rch & RM=5528,127,27733.35
11635.1518057.42 23985.229032.8542387.9638804.79
River Rch & RM=5528,127,27487.68
11638.14 18062.323991.8929041.1742400.11   38815
River Rch & RM=5528,127,27242.01
16265.0825528.0234167.9841627.1160775.5753627.97
River Rch & RM=5528,127,26996.34
16270.8225537.3734180.7941643.0360798.8353646.48
River Rch & RM=5528,127,26750.68
16272.9625540.8334185.5541648.9560807.4653653.36
River Rch & RM=5528,127,26505.01
16281.7425555.1734205.2341673.4460843.2253681.91
River Rch & RM=5528,127,26259.34
16287.7325564.9634218.68 41690.260867.6953701.46
River Rch & RM=5528,127,26179.75
16289.5325567.89 34222.741695.1960874.9853707.29
River Rch & RM=5528,127,25930.31
16305.8125594.3734258.9941740.27 60940.8 53759.6
River Rch & RM=5528,127,25680.86
16311.0625602.9134270.6941754.8360962.0553776.51
River Rch & RM=5528,127,25431.41
16318.5525615.1334287.46 41775.760992.5253800.81
River Rch & RM=5528,127,25181.97
16330.2725634.2534313.7141808.35 61040.253838.84
River Rch & RM=5528,127,24932.52
16336.9525645.1434328.6641826.9561067.3553860.49
River Rch & RM=5528,127,24683.08
16340.0225650.1634335.5541835.5461079.8853870.52
River Rch & RM=5528,127,24433.63
16343.71 25656.234343.8741845.9161095.0453882.66
River Rch & RM=5528,127,24232.12
16345.7925659.6234348.5741851.7761103.5953889.52
River Rch & RM=5528,127,23984.22
16380.0125715.71 34425.841948.1461244.2954002.45
River Rch & RM=5528,127,23702.76
16405.7825758.0934484.2642021.2161350.9654088.39
River Rch & RM=5528,127,23435.85
   1641225768.2934498.3242038.7561376.5754108.95
River Rch & RM=5528,127, 23186.4
16432.8225802.55 34545.642097.8661462.8854178.51
River Rch & RM=5528,127,22936.96
16436.1825808.0634553.1842107.3261476.6854189.57
River Rch & RM=5528,127,22687.51
16440.0325814.3634561.8442118.1261492.4554202.21
River Rch & RM=5528,127,22438.07
16440.9825815.9334564.0142120.82 61496.454205.37
River Rch & RM=5528,127,22157.73
16451.1425832.61   3458742149.5461538.3254239.07
River Rch & RM=5528,127,21939.17
16453.1925835.9834591.6642155.3661546.8254245.91
River Rch & RM=5528,127,21689.73
16473.0525868.4334636.2542210.8961627.9154310.66
River Rch & RM=5528,127,21440.28
16476.2125873.6334643.4242219.8561640.9854321.19
River Rch & RM=5528,127,21235.56
16478.7625877.8134649.1842227.0461651.4854329.61
River Rch & RM=5528,127,20941.39
16489.5525895.4634673.4342257.26 61695.654364.86
River Rch & RM=5528,127,20691.95
16491.6325898.8634678.1342263.1161704.15 54371.7
River Rch & RM=5528,127,20193.05
 16496.725907.19 34689.642277.4561725.0854388.53
River Rch & RM=5528,127,19943.61
16499.2225911.3434695.3342284.6161735.5354396.95
River Rch & RM=5528,127,19767.85
16514.2825936.1534729.5942327.4761798.1154447.43
River Rch & RM=5528,127,19510.79
17011.2626736.1635818.84 43673.163762.7355980.52
River Rch & RM=5528,127,19195.27
17015.9326743.8635829.4743686.4163782.1755996.12
River Rch & RM=5528,127,18945.83
17022.1226754.07 35843.6 43704.163807.9856016.92
River Rch & RM=5528,127,18696.38
17061.4626819.0735933.5343816.7763972.4956149.44
River Rch & RM=5528,127,18446.93
17064.4926824.1135940.5243825.5663985.3256159.82
River Rch & RM=5528,127,18197.49
17067.9826829.9135948.5743835.6664000.0756171.77
River Rch & RM=5528,127,17948.04
 17081.726852.5735979.9243874.9564057.4356217.99
River Rch & RM=5528,127, 17698.6
17086.5826860.6635991.1343889.0364077.98 56234.6
River Rch & RM=5528,127,17449.15
17090.0526866.4435999.1643899.1164092.7156246.54
River Rch & RM=5528,127,17248.87
 17094.626873.9936009.6443912.2864111.9356262.11
River Rch & RM=5528,127,16950.26
17161.7926985.6836164.73 44107.264396.5256492.89
River Rch & RM=5528,127,16700.81
17176.9427010.9836199.96 44151.664461.3456545.74
River Rch & RM=5528,127,16451.37
17180.2427016.4836207.59 44161.264475.3656557.14
River Rch & RM=5528,127,16201.92
17197.3927045.08 36247.444211.3164548.52 56616.7
River Rch & RM=5528,127,15952.48
 17210.9 27067.536278.4944250.3664605.5356662.77
River Rch & RM=5528,127,15703.03
17215.0927074.48 36288.244262.5864623.3756677.26
River Rch & RM=5528,127,15453.59
 17218.727080.4836296.5444273.0664638.6756689.68
River Rch & RM=5528,127, 15044.8
17270.2727165.8236414.7144421.2564855.0256863.96
River Rch & RM=5528,127, 14455.8
17961.4428305.6537990.0846393.3167734.2359166.02
River Rch & RM=5528,127,13956.91
17966.6328314.2838002.0946408.43 67756.359183.83
River Rch & RM=5528,127,13707.47
17968.2428316.9738005.8446413.15 67763.259189.43
River Rch & RM=5528,127,13458.02
17970.8728321.3838011.9846420.89 67774.559198.59
River Rch & RM=5528,127,13208.57
 17973.528325.7938018.1246428.63 67785.859207.75
River Rch & RM=5528,127,12959.13
 17975.728329.4638023.2446435.0867795.2259215.38
River Rch & RM=5528,127,12709.68
17978.9328334.8538030.7546444.5567809.0559226.57
River Rch & RM=5528,127,12210.79
17981.5628339.2538036.8846452.2867820.3459235.73
River Rch & RM=5528,127, 11711.9
 18743.329600.8639785.33 48646.271023.4561794.03
River Rch & RM=5528,127,11462.45
 18744.929603.5339789.0448650.89 71030.361799.53
River Rch & RM=5528,127,11213.01
18747.2229607.4139794.45 48657.771040.2361807.53
River Rch & RM=5528,127,10714.12
18757.0829623.8839817.3948686.6371082.4861841.54
River Rch & RM=5528,127,10215.22
18761.5429631.3539827.8248699.79 71101.761857.04
River Rch & RM=5528,127,9965.779
18965.0529975.2440310.1649311.3271994.5262584.46
River Rch & RM=5528,127,9716.333
18967.3429979.0740315.5149318.08 72004.462592.42
River Rch & RM=5528,127,9466.888
18968.7729981.4740318.87 49322.372010.57 62597.4
River Rch & RM=5528,127,9217.442
18978.5329997.8140341.6649351.0972052.5962631.24
River Rch & RM=5528,127,8967.996
18987.1330012.2240361.7749376.4672089.6462661.09
River Rch & RM=5528,127, 8718.55
 18988.730014.8540365.4549381.1272096.4362666.57
River Rch & RM=5528,127,8469.105
18994.0630023.8840378.0849397.0972119.7562685.47
River Rch & RM=5528,127,8219.659
19002.1130037.4140397.0249421.0772154.7662713.82
River Rch & RM=5528,127,8018.056
19004.1130040.7740401.7149426.98 72163.462720.79
River Rch & RM=5528,127,7720.767
 19066.730146.3440549.6449614.38   7243762942.95
River Rch & RM=5528,127,7471.322
19069.6830151.3640556.6549623.2472449.9462953.38
River Rch & RM=5528,127,7221.876
19074.7830159.9340568.6349638.3972472.0562971.25
River Rch & RM=5528,127, 6972.43
19078.9130166.8640578.3149650.61 72489.962985.65
River Rch & RM=5528,127,6722.984
19091.0130187.1640606.6749686.44 72542.263027.85
River Rch & RM=5528,127,6473.539
 19095.330194.34 40616.749699.11 72560.763042.74
River Rch & RM=5528,127,6224.093
19181.5330338.4440817.4949952.2872930.3363339.28
River Rch & RM=5528,127,6010.271
19185.1230344.4440825.8749962.8472945.7563351.66
River Rch & RM=5528,127,5725.202
19221.7530405.7740911.4450070.8573103.4463478.44
River Rch & RM=5528,127,5475.756
19226.0530412.9840921.4950083.5273121.9563493.29
River Rch & RM=5528,127, 5226.31
19231.2230421.6340933.5550098.7373144.1663511.11
River Rch & RM=5528,127,4976.864
19243.3130441.8340961.7150134.2473195.9963552.68
River Rch & RM=5528,127,4727.419
 19247.530448.8240971.4550146.5273213.9163567.02
River Rch & RM=5528,127,4477.973
19266.1830479.9841014.8350201.1573293.6963630.83
River Rch & RM=5528,127,4228.527
19269.5130485.5441022.5650210.8973307.91 63642.2
River Rch & RM=5528,127,3979.081
19277.1730498.3241040.3650233.3273340.65 63668.4
River Rch & RM=5528,127,3676.105
19279.4830502.1841045.73 50240.173350.5563676.32
River Rch & RM=5528,127,2981.298
19280.7830504.3641048.7650243.9173356.1163680.77
Boundary for River Rch & Prof#=5528,127,1
Up Type= 0
Dn Type= 2
Boundary for River Rch & Prof#=5528,127,2
Up Type= 0
Dn Type= 2
Boundary for River Rch & Prof#=5528,127,2
Up Type= 0
Dn Type= 2
Boundary for River Rch & Prof#=5528,127,2
Up Type= 0
Dn Type= 2
Boundary for River Rch & Prof#=5528,127,2
Up Type= 0
Dn Type= 2
Boundary for River Rch & Prof#=5528,127,2
Up Type= 0
Dn Type= 2

--- 5528_ras.g01 (geometry) ---

Geom Title=5528
Program Version=4.10

River Reach=5528,127
Reach XY= 30
472713.023942828796744.143568739 474715.17137298796641.608431086
475575.414485961796222.337863192475373.157563776797770.948917016
476282.879941285797159.837789923477330.622867495797123.379346758
477407.011926681798589.525115833479009.677618027797836.610173821
479539.824423283798371.643443212479908.747758061799902.893440351
480978.192391694799759.664250568480536.352005452 800416.78228426
480730.796412766800738.830593616480092.775572479801139.872379661
480032.879810184801928.067075148480725.588113248801902.893214688
481607.532634109802676.330761954482538.956293881802561.747630864
483237.741028041803114.698933795 485025.93544057801744.039264932
484920.900636733802737.962641716486012.046359777802514.872354046
485097.983888835803476.678187922485699.546525717803666.782265723
485443.470273435804358.622439116485899.199153125804828.240433455
484499.025652736808636.400103673483004.980643362808917.663922787
482563.345000267810821.961543351481875.798233837810910.630804867

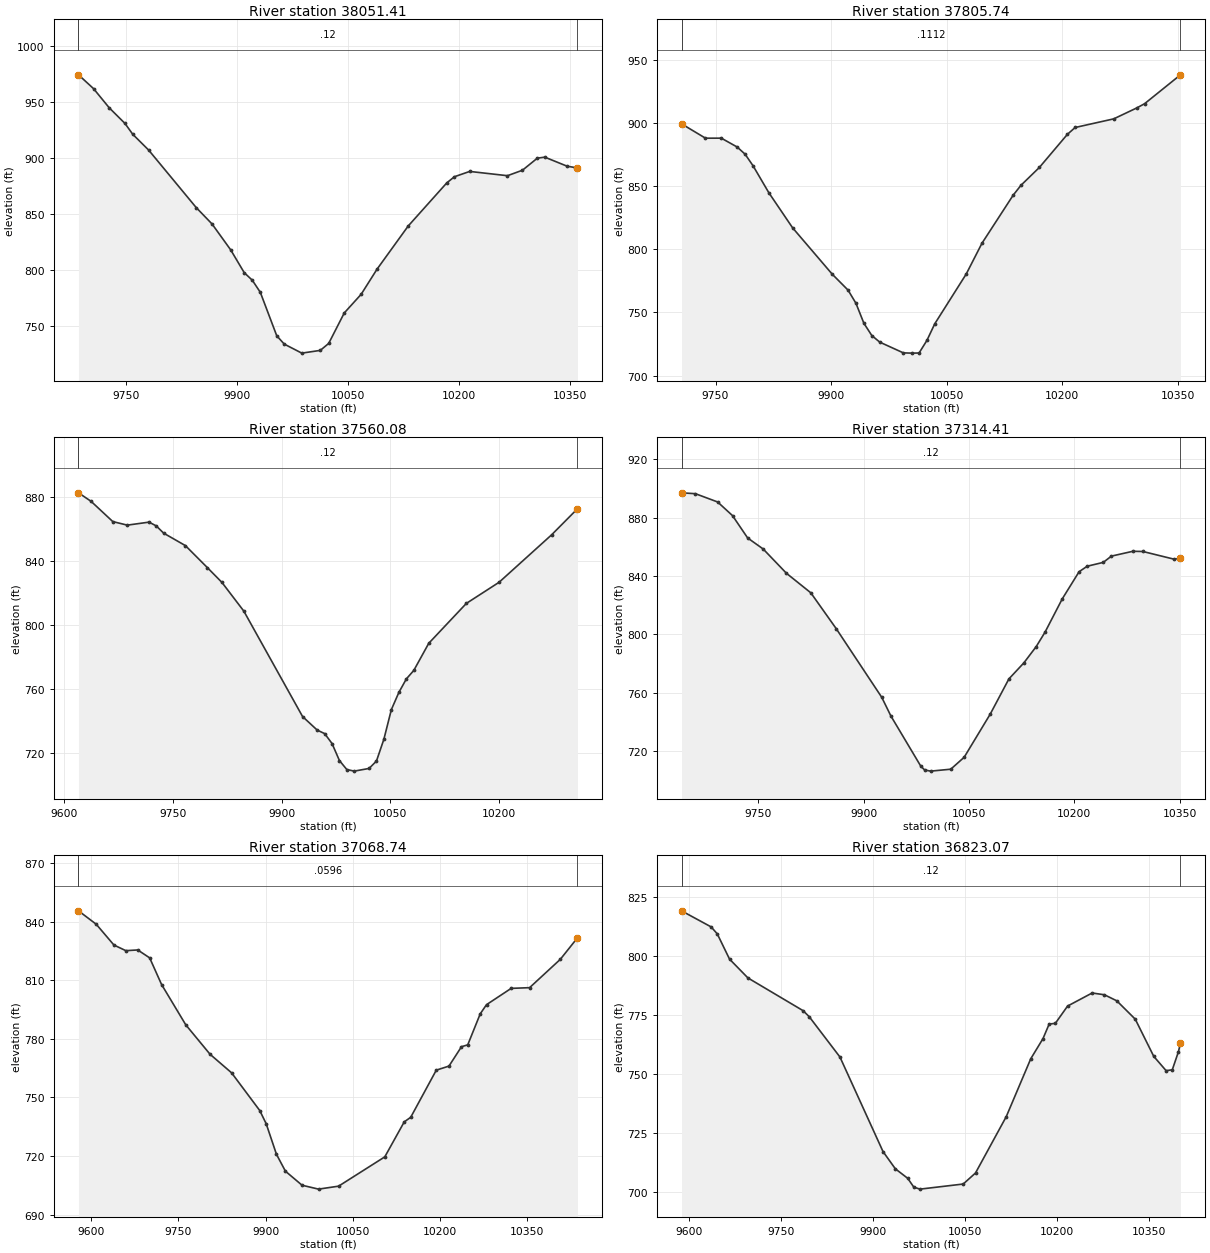
Type RM Length L Ch R = 1 ,38051.41,245.668200,245.668200,245.668200
XS GIS Cut Line= 6
472591.845573041797034.203255827472653.303673146796869.278655746
472746.560528871796680.338718019472773.435096125796602.803945563
472799.813150454796487.124188241472809.776319792796401.103535179
#Sta/Elev= 30
9685.325973.95239705.699961.64359726.918944.55719748.137930.68989758.762920.9647
9780.195906.94569844.496855.73979865.996841.06829891.155818.05639909.482797.7106
9920.354791.02829931.226780.23899953.479741.48759963.633734.08969987.353726.0487
 10012.3728.4784 10023.7734.667310044.76 761.82610067.62778.451710088.98800.7173
10131.31839.329610183.49877.736310193.81883.191310214.44887.897810265.49884.0972
10285.75888.964610305.94899.731110316.03 900.60610346.21892.552610360.14891.0086
#Mann= 3 , 0 , 0
9685.325    0.12       09685.325    0.12       010360.14    0.12       0
#XS Ineff= 2 , 0
       0                               0
Bank Sta=9685.325,10360.14
Exp/Cntr=0.3,0.1

Type RM Length L Ch R = 1 ,37805.74,245.668100,245.668100,245.668100
XS GIS Cut Line= 6
472877.146951139 797115.25478368472938.509753056796856.959406939
472965.032231761  796724.8198947472974.019686002 796661.29040177
472979.131611509796582.909259106 472977.37250656796478.455621379
#Sta/Elev= 30
9705.842899.25039736.938887.88159757.495887.90949778.052   880.9 9788.33875.2365
9798.608866.11389819.165 844.728    9850816.96929901.392780.31059921.948767.6972
9932.227757.24069942.505741.45329952.783731.76779963.061726.55259993.715718.0487
10004.95  717.85 10014.1717.9511 10024.3727.9252 10034.5741.092410075.31780.4499
10095.72804.777510136.22842.803410146.32850.613410170.26864.769310206.63890.9647
10216.65 896.34510266.72903.171410296.72911.849310306.72915.1461 10353.3938.0052
#Mann= 3 , 0 , 0
9705.842  0.1112       09705.842  0.1112       0 10353.3  0.1112       0
#XS Ineff= 2 , 0
       0                               0
Bank Sta=9705.842,10353.3
Exp/Cntr=0.3,0.1

Type RM Length L Ch R = 1 ,37560.08,245.668200,245.668200,245.668200
XS GIS Cut Line= 6
473230.783285729 797212.34851147473224.541634488797080.198280157
473211.615707065796976.155092613473195.646662746796883.708814695
473158.127129009796722.080377847473105.351172559796537.540693227
#Sta/Elev= 30
9619.641882.4946 9636.99877.20439667.013864.55579687.028862.33669717.087864.2141
9727.116861.82739737.145857.36669767.305849.55629797.536835.8644 9817.69826.6185
 9847.92808.71099929.042742.93939949.338734.45159959.531732.30129969.731726.1079
9979.931715.48219990.131709.891110000.33708.891110020.82710.557510031.07715.1885
10041.31728.790510051.64747.272110061.97757.9673 10072.3766.391710082.62771.7077
10103.28788.6389 10155.2813.522810200.42826.711810272.88856.290510308.56872.5319
#Mann= 3 , 0 , 0
9619.641    0.12       09619.641    0.12       010308.56    0.12       0
#XS Ineff= 2 , 0
       0                               0
Bank Sta=9619.641,10308.56
Exp/Cntr=0.3,0.1

Type RM Length L Ch R = 1 ,37314.41,245.668200,245.668200,245.668200
XS GIS Cut Line= 6
473569.707176337797014.110009421 473543.35194848796932.737745062
473496.396479341796840.828073915 473428.55415393796754.507076455
473272.248176182796585.468512757473186.911424486796426.349779242
#Sta/Elev= 30
9640.872896.96449660.689896.3687 9692.28890.70049713.463881.36499735.002866.0726
9757.108858.51469790.267841.87689824.915828.52679861.197 803.9119925.918756.9714
9939.027744.10069981.466709.86339987.053707.2024 9995.63706.442810024.16707.7595
 10043.2715.911610080.25745.390710106.93769.585110128.16780.5102 10145.8791.7039
10158.32801.541510182.84824.337910206.82842.935310218.33846.708510241.29849.3566
10252.84853.635510283.36856.944310297.71856.798210341.66851.583710351.16852.0965
#Mann= 3 , 0 , 0
9640.872    0.12       09640.872    0.12       010351.16    0.12       0
#XS Ineff= 2 , 0
       0                               0
Bank Sta=9640.872,10351.16
Exp/Cntr=0.3,0.1

Type RM Length L Ch R = 1 ,37068.74,245.668200,245.668200,245.668200
XS GIS Cut Line= 6
473699.901808717 796945.23304343473670.347634501 796799.70287317
473620.140679501796651.055433453473488.796384884796400.042435644
473441.736255871796287.051024712473394.155420409796146.822195946
#Sta/Elev= 30
9577.835845.56789608.464838.67869638.888828.0475 9659.41825.16389679.932825.5278
9700.454821.46999720.976807.81759762.685787.16629804.496772.09529841.539762.6058
9890.093743.2831 9901.15736.53729918.886720.8632 9934.32712.21059962.976705.0164
9991.366703.0231 10025.9704.539510105.51719.5514   10139737.472910150.16739.8192
 10194.2763.960310216.05766.042610237.63775.9766 10248.4776.918910269.94792.8273
10280.71797.493110323.19805.847710354.93 806.21110407.84820.715610437.37831.7256
#Mann= 3 , 0 , 0
9577.835  0.0596       09577.835  0.0596       010437.37  0.0596       0
#XS Ineff= 2 , 0
       0                               0
Bank Sta=9577.835,10437.37
Exp/Cntr=0.3,0.1

Type RM Length L Ch R = 1 ,36823.07,245.668200,245.668200,245.668200
XS GIS Cut Line= 6
473787.815997656  796943.2793948 473788.55668958796685.480206338
473812.054980158796418.985491113473812.728480623796340.676990769
473809.018212759796261.689212346 473795.28450802796131.779855153
#Sta/Elev= 30
9587.285819.35129635.565812.53819645.566809.58819665.566798.88919695.567790.9052
9785.576777.02459795.578774.45279845.589757.39019915.791717.33199935.911710.0148
9956.031706.00199966.091702.21739976.152701.411410046.53703.572210066.57708.2494
10116.67732.114310156.67756.670210176.67765.235610186.67 771.37410196.68 771.655
 10216.7778.995110256.75 784.53210276.79783.774310296.89781.215510327.03 773.431
10357.18757.673210377.28751.623110387.36751.968110397.47759.677210400.72763.3697
#Mann= 3 , 0 , 0
9587.285    0.12       09587.285    0.12       010400.72    0.12       0
#XS Ineff= 2 , 0
       0                               0
Bank Sta=9587.285,10400.72
Exp/Cntr=0.3,0.1

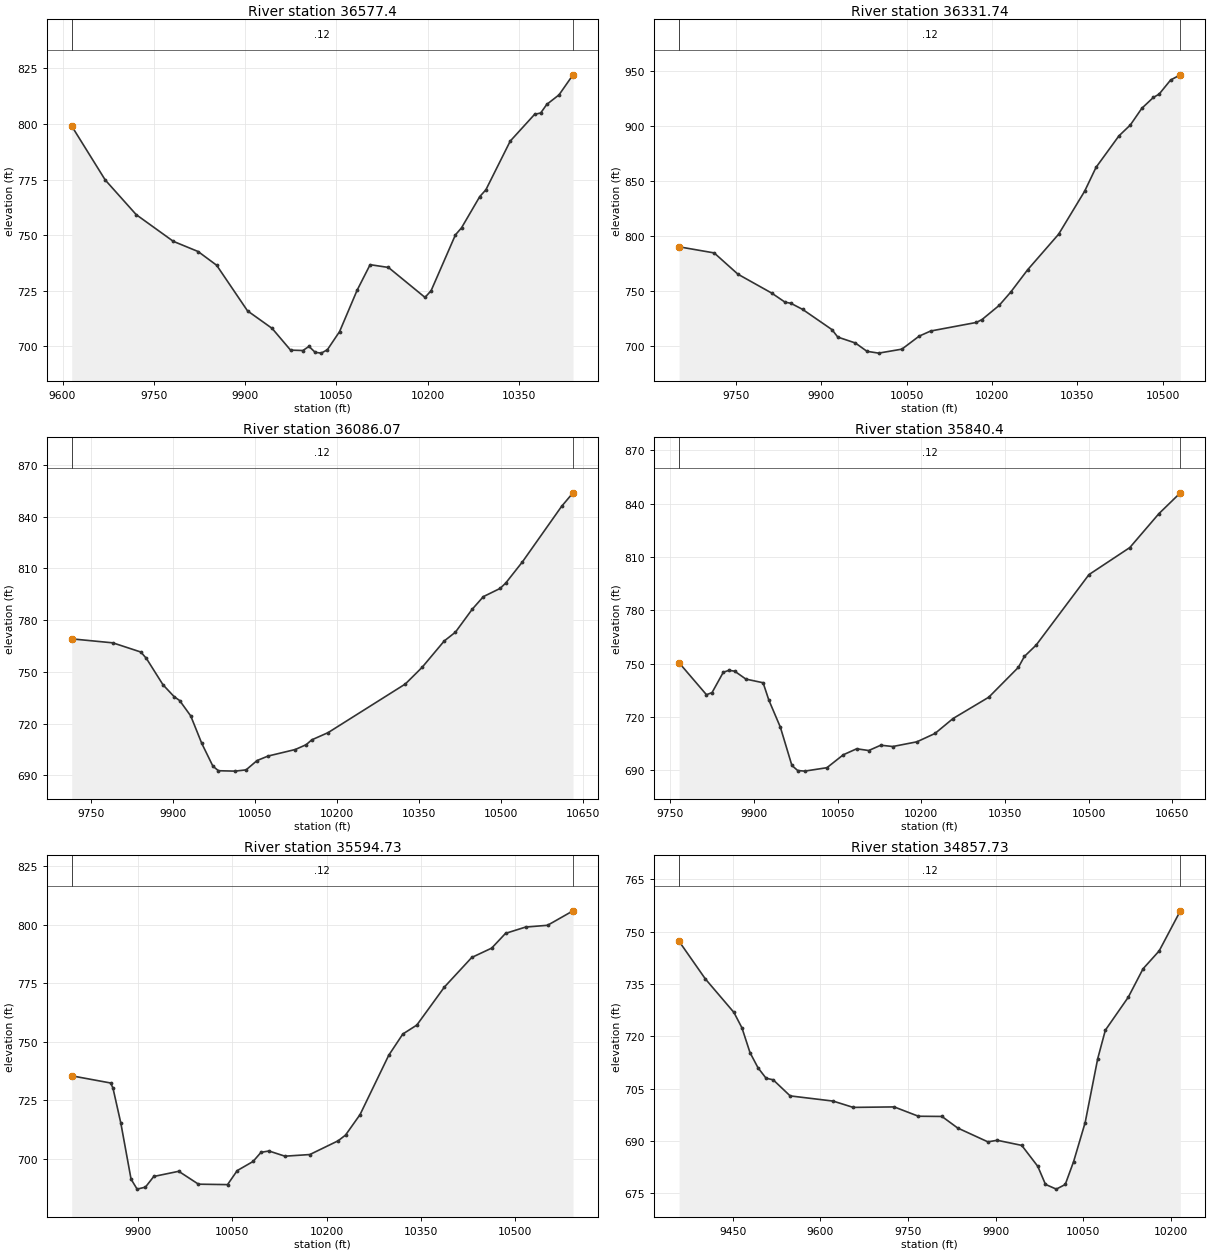
Type RM Length L Ch R = 1 , 36577.4,245.668200,245.668200,245.668200
XS GIS Cut Line= 6
473980.405735778796938.999622858474031.793507629796665.063693082
474050.434640811796531.577573114474062.752914756796343.683240978
474062.613792199796278.339624383474052.927535599796122.118241609
#Sta/Elev= 30
9615.166799.06119670.249 774.7849721.172759.17949782.154747.16369822.809742.5853
9853.301736.4025 9904.06715.85959944.481707.97069974.797698.17999995.007698.0077
10005.09699.863310015.16697.197510025.23696.830310035.28698.361910055.35706.5357
10084.16725.155510105.52736.657210135.62735.4123 10195.7721.925110205.71724.9209
10245.71750.086410255.71753.244510285.72767.331710295.73770.362210335.78792.3067
10375.82804.346310385.83  804.9710395.85808.834210415.94813.120310438.93822.1448
#Mann= 3 , 0 , 0
9615.166    0.12       09615.166    0.12       010438.93    0.12       0
#XS Ineff= 2 , 0
       0                10102.94       0
Bank Sta=9615.166,10438.93
Exp/Cntr=0.3,0.1

Type RM Length L Ch R = 1 ,36331.74,245.668200,245.668200,245.668200
XS GIS Cut Line= 6
474200.352388285796934.111919455474267.948376202796689.755101492
 474296.86404191796561.945809023474309.778379219796469.485137529
474311.454522651796280.502776059474286.334867983796068.075026911
#Sta/Elev= 30
9649.868789.99459711.588784.4376 9753.33765.12749812.588748.00319836.011739.7586
9846.346738.71439867.016733.16299918.596714.80739928.867708.01279959.678 702.665
9980.219 695.07710000.75693.444710041.53697.063410071.93708.895810092.12713.5272
10172.47721.310510182.47723.975410212.49736.7711 10232.5748.650210262.51769.0997
10317.03801.451610362.75840.470410382.84862.178510423.03890.733310443.12900.6443
10463.34915.812810483.56925.632810493.67928.6395 10513.9941.474910531.01946.1787
#Mann= 3 , 0 , 0
9649.868    0.12       09649.868    0.12       010531.01    0.12       0
#XS Ineff= 2 , 0
       0                               0
Bank Sta=9649.868,10531.01
Exp/Cntr=0.3,0.1

Type RM Length L Ch R = 1 ,36086.07,245.668200,245.668200,245.668200
XS GIS Cut Line= 6
474470.906316543796927.579136841474503.092613572796800.771576294
474532.610446286796634.583113436474537.573794872796508.151390047
474518.017695704796340.193944112474451.086484624796024.598905861
#Sta/Elev= 30
9714.221769.13749789.559766.8244 9840.79   761.59850.978757.79779881.438742.4896
9901.745735.63659911.898733.36639932.204724.44459952.511708.44449972.817695.2913
 9982.97692.646910013.49692.4158 10033.6693.1434 10053.7698.551210073.72701.1473
10123.74704.960810143.75707.765310153.77710.535710183.83714.751410325.26742.9554
10355.81752.536610396.56767.915410417.03773.008710447.74 786.28510468.22793.6276
10498.93798.399310509.17801.502710539.88813.836810611.54845.997810632.43853.8465
#Mann= 3 , 0 , 0
9714.221    0.12       09714.221    0.12       010632.43    0.12       0
#XS Ineff= 2 , 0
       0                               0
Bank Sta=9714.221,10632.43
Exp/Cntr=0.3,0.1

Type RM Length L Ch R = 1 , 35840.4,245.668200,245.668200,245.668200
XS GIS Cut Line= 6
474811.157011094 796854.01141909 474810.05460194796790.196832048
474799.607869264796726.936916164474772.214851916796623.451532849
 474618.96660827796220.686097914474552.756483379 795997.76932284
#Sta/Elev= 30
9765.925750.4897 9815.01732.50459825.016733.69629845.225  745.16 9855.36746.2239
9865.496745.76729885.766741.29349916.577 739.2419926.897729.45779947.537714.2189
9968.177692.7089 9978.56689.84669991.054689.502110031.01691.433710060.32698.6987
10084.32 702.07410105.92701.098410127.52704.087910149.12703.353510192.32706.0005
10224.72710.687510257.12719.1052 10321.2731.112410374.34747.946410384.97754.0253
10406.23 760.483 10500.8800.105710574.06815.331210626.13834.389610664.65846.1329
#Mann= 3 , 0 , 0
9765.925    0.12       09765.925    0.12       010664.65    0.12       0
#XS Ineff= 2 , 0
       0                               0
Bank Sta=9765.925,10664.65
Exp/Cntr=0.3,0.1

Type RM Length L Ch R = 1 ,35594.73,737.004500,737.004500,737.004500
XS GIS Cut Line= 6
475087.964083126796640.005445485475038.893298665796566.791438854
474870.542000758796365.460112761474818.636367854796285.381827965
474742.670367281796130.542010728 474682.88526431 795963.42978343
#Sta/Elev= 30
9795.062735.48149856.775732.41729860.511730.31049873.073715.2702 9889.34691.2954
9898.969687.04699912.185687.9035  9925.4692.45759965.048  694.679996.406689.1622
 10042.6688.975810057.98694.966110083.14698.863510095.81702.775910108.48703.3449
10133.81 701.12910173.34701.829910218.29707.704210230.05710.140510253.17718.9248
10298.72744.269610321.12 753.35410343.34757.173910387.24773.455810430.64786.0771
10462.23790.064310484.28796.368210516.08799.061310551.08799.829810591.48806.0088
#Mann= 3 , 0 , 0
9795.062    0.12       09795.062    0.12       010591.48    0.12       0
#XS Ineff= 2 , 0
       0                               0
Bank Sta=9795.062,10591.48
Exp/Cntr=0.3,0.1

Type RM Length L Ch R = 1 ,34857.73,491.336400,491.336400,491.336400
XS GIS Cut Line= 6
475144.071284175796703.225423068475310.663904279796527.422941193
475375.760177016796452.503330946475640.978518873796204.923833787
475690.143731505 796146.77213116 475736.37548244796083.373300791
#Sta/Elev= 30
9357.673747.19659402.638736.42979451.665726.81169465.442  722.389479.219715.2959
9492.995710.92369506.772707.94869518.945707.49329548.022702.88399621.728701.3919
9656.071699.58789726.312 699.7259767.845697.04949808.152696.99369835.023693.6889
9886.851689.71149902.964690.15869944.904688.69659972.427682.68269985.575677.5171
10004.11676.156710019.45677.486310033.84684.0705 10053.6695.2543 10075.1713.5515
10088.19721.722710127.48731.177210152.82739.325110180.44744.454110216.72 755.936
#Mann= 3 , 0 , 0
9357.673    0.12       09357.673    0.12       010216.72    0.12       0
#XS Ineff= 2 , 0
       0                               0
Bank Sta=9357.673,10216.72
Exp/Cntr=0.3,0.1

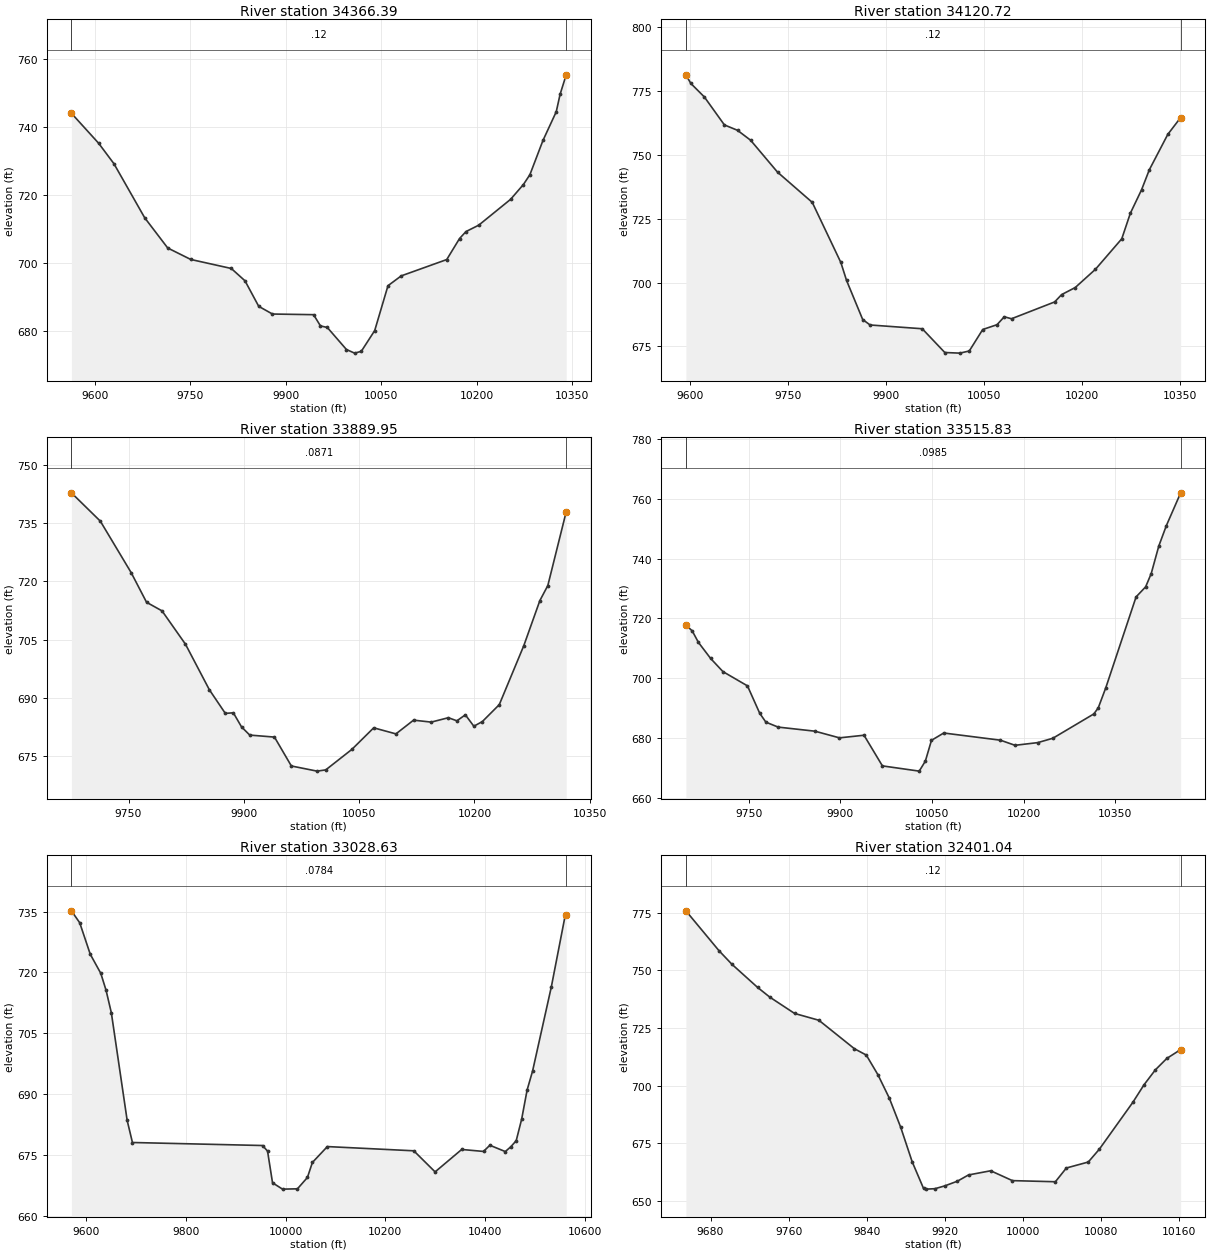
Type RM Length L Ch R = 1 ,34366.39,245.668200,245.668200,245.668200
XS GIS Cut Line= 6
475189.601595134796724.906523511475345.220833647796619.718655783
475578.006584111796710.218210264475712.776491298796747.168450474
475797.794406584796753.912381873475909.618692138796731.361603206
#Sta/Elev= 30
 9563.34744.12079606.066735.30299630.207729.24949678.487713.33249714.698704.4218
9750.908701.04229814.633 698.3829836.187694.74159857.741687.22519879.295684.9597
9943.956684.76839954.733681.4562 9965.51680.9997  9995.6674.497710008.37673.4382
10018.91673.960310039.99680.083810060.87693.306810081.66696.199510153.21701.0112
10173.36 707.21410183.44709.257510203.47711.1408 10253.6718.765510273.69723.1218
10283.91726.019610304.42736.104510325.32744.573710331.36749.714510340.94755.4475
#Mann= 3 , 0 , 0
 9563.34    0.12       0 9563.34    0.12       010340.94    0.12       0
#XS Ineff= 2 , 0
       0                               0
Bank Sta=9563.34,10340.94
Exp/Cntr=0.3,0.1

Type RM Length L Ch R = 1 ,34120.72,230.768000,230.768000,230.768000
XS GIS Cut Line= 6
 475098.30589198796818.864919768475171.464673323796804.221207022
475272.780222897796828.414118242475660.794115774797016.296581853
475728.113427899797021.319881844475799.061029153796993.424211775
#Sta/Elev= 30
9593.758781.39659601.305778.03269622.102772.70039652.662761.77589672.706759.6701
9692.833755.76429733.918743.28359787.064731.43799830.793707.89499839.499700.8739
9864.189685.56869875.475683.42419955.288681.94719989.793672.639210012.74672.4006
10027.22673.239510047.79681.651410069.66683.536210080.75686.636210091.84685.8648
10157.77692.443510168.47695.322910189.34698.098410220.26705.250810260.47717.1793
10273.59727.182110290.85736.438610302.58744.188510330.85758.068810350.57764.6764
#Mann= 3 , 0 , 0
9593.758    0.12       09593.758    0.12       010350.57    0.12       0
#XS Ineff= 2 , 0
       0                               0
Bank Sta=9593.758,10350.57
Exp/Cntr=0.3,0.1

Type RM Length L Ch R = 1 ,33889.95,374.123100,374.123100,374.123100
XS GIS Cut Line= 6
 475047.60678862 797064.70062374475158.463041521 797063.85589229
475253.009490861797086.314436513475341.985025312797122.800191993
475565.544119992797239.841280347 475648.74534058797261.593622749
#Sta/Elev= 30
9675.677742.78129713.311735.4956 9753.38722.26769773.431714.63179793.578 712.416
9824.093 703.8369855.102692.14489875.884686.0568 9886.33686.20469896.999682.5726
9907.667680.47389939.847679.95519961.792672.5272 9995.19671.201810006.53671.5182
10040.56676.799810068.93682.338910097.85680.780510120.78684.314510143.71 683.809
10166.09684.940110177.12684.141810188.16685.6783 10199.2682.752610210.23683.9431
 10232.3688.307210264.22703.495710285.11715.083510295.42718.928110319.32737.9074
#Mann= 3 , 0 , 0
9675.677  0.0871       09675.677  0.0871       010319.32  0.0871       0
#XS Ineff= 2 , 0
       0                               0
Bank Sta=9675.677,10319.32
Exp/Cntr=0.3,0.1

Type RM Length L Ch R = 1 ,33515.83,487.202000,487.202000,487.202000
XS GIS Cut Line= 3
474944.605160087797518.434799775475395.572049409797481.576929018
475683.930685252797271.270254716
#Sta/Elev= 30
9647.377717.80249657.807715.7659 9667.84711.95059687.907706.55739707.973702.1729
9748.107697.39779768.173688.22559778.207685.26439798.274683.60829858.474682.2405
9898.607680.0102 9938.74680.8869 9968.84670.633510029.04668.879110039.07672.2095
10049.11679.182710069.17681.632310161.92679.226110185.78677.517610222.91678.4142
10247.66679.874510314.66688.008410321.93690.0383 10334.3696.791310383.81 727.161
10399.51730.547210408.57 734.97410420.94744.170910433.32750.999810456.75761.9764
#Mann= 3 , 0 , 0
9647.377  0.0985       09647.377  0.0985       010456.75  0.0985       0
#XS Ineff= 2 , 0
       0                               0
Bank Sta=9647.377,10456.75
Exp/Cntr=0.3,0.1

Type RM Length L Ch R = 1 ,33028.63,627.584200,627.584200,627.584200
XS GIS Cut Line= 6
475432.429920107798270.768985212475538.667312294797962.897358909
475540.835422337797767.767454907 475518.87134847797630.300387651
475562.516522765 797514.09857969475647.072814494797323.304895774
#Sta/Elev= 30
 9570.18735.17339586.861 732.2299608.018724.47239629.175719.75769639.754715.5745
9650.333710.03839682.069683.50199692.647678.06179953.766677.31779963.767675.9396
9973.768 668.1299993.769666.567810023.77666.642610043.77669.439610053.77673.1422
10083.77677.056810257.24676.015410299.97670.817310353.38676.345310397.11675.8603
10409.84677.382110440.86675.8265 10451.8677.003210462.74678.506810473.68683.8207
10484.62691.000610495.55695.656610533.24716.436210561.18734.125510563.04734.0909
#Mann= 3 , 0 , 0
 9570.18  0.0784       0 9570.18  0.0784       010563.04  0.0784       0
#XS Ineff= 2 , 0
       0                               0
Bank Sta=9570.18,10563.04
Exp/Cntr=0.3,0.1

Type RM Length L Ch R = 1 ,32401.04,245.668200,245.668200,245.668200
XS GIS Cut Line= 6
476119.886965226797621.316623624476070.675184782797577.100259488
475969.713007654797503.479084644 475906.35714783797465.113816225
475769.840404485797396.760660808475692.894420811 797352.38267791
#Sta/Elev= 30
9654.785775.82139688.724758.53319701.979752.64169728.148742.66799740.706738.4326
9766.118731.35429791.031728.39579827.426716.05729839.558713.32419851.482704.8087
9863.172 694.6589874.863 681.9939886.553667.10939898.244655.49919900.953655.2199
9909.934655.40619920.038656.63159932.936 658.6649944.293661.36439967.006663.1738
9989.262658.9025 10033.3658.420710044.53664.376310066.99666.964210078.32672.5271
10112.64692.842710124.08700.4401 10135.7706.905610147.43711.860810161.63715.7004
#Mann= 3 , 0 , 0
9654.785    0.12       09654.785    0.12       010161.63    0.12       0
#XS Ineff= 2 , 0
       0                               0
Bank Sta=9654.785,10161.63
Exp/Cntr=0.3,0.1

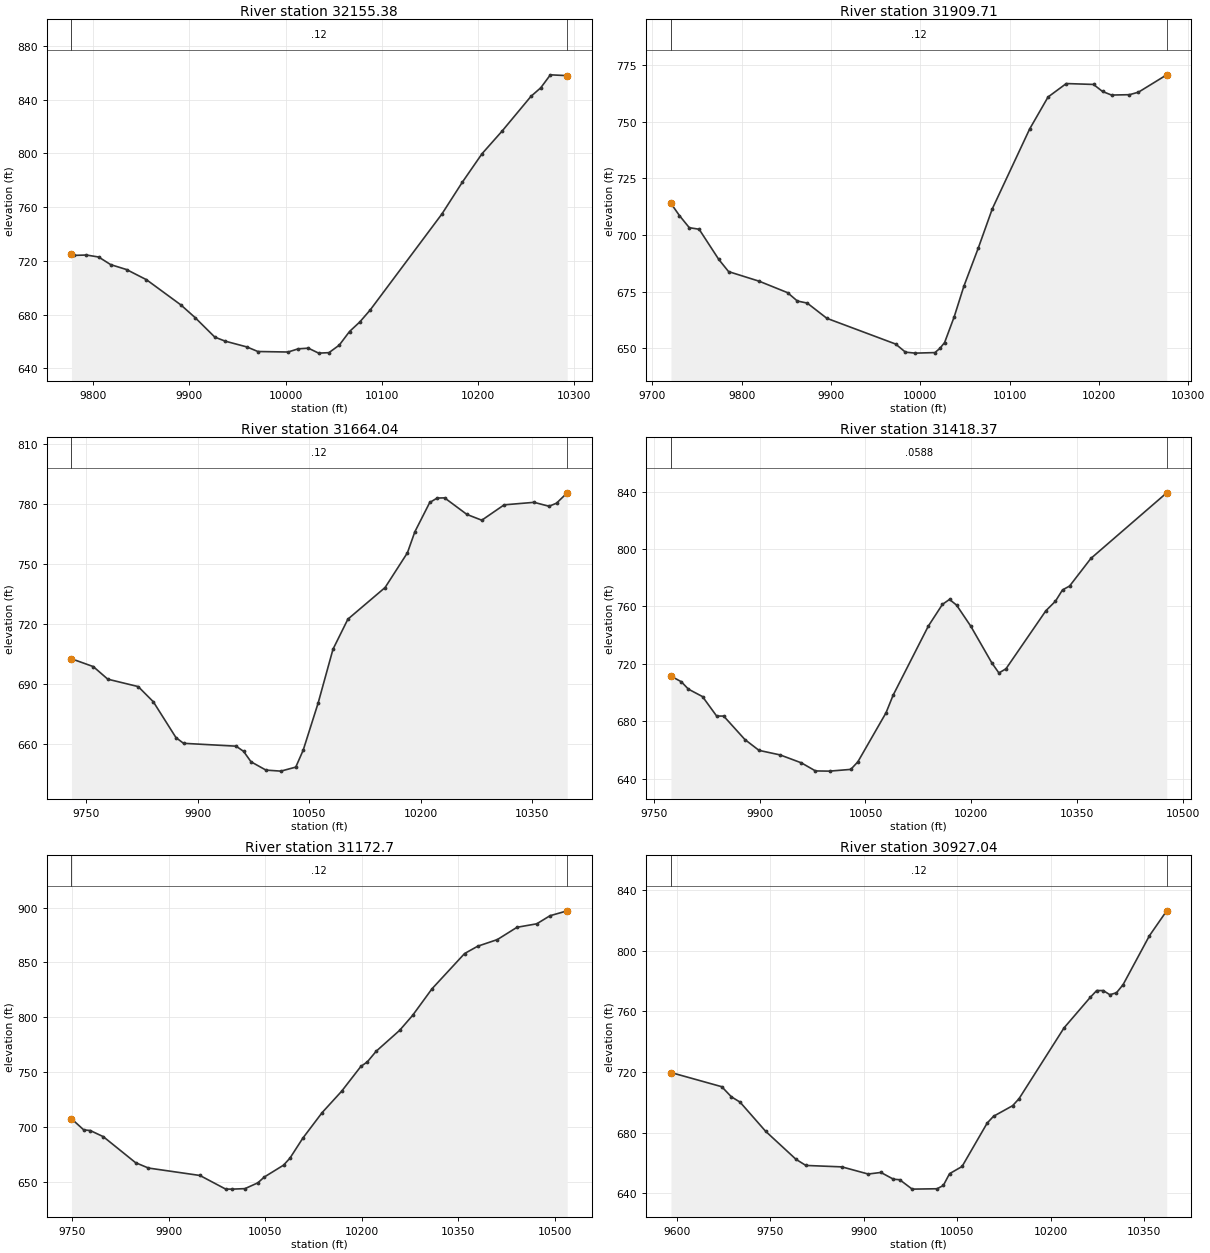
Type RM Length L Ch R = 1 ,32155.38,245.668200,245.668200,245.668200
XS GIS Cut Line= 6
476139.729773018797487.352078552 476090.38761947797421.819663177
476038.450072716797332.963122918475961.348305172797124.146377359
475951.598644925797086.789587508475943.507180358797017.503608739
#Sta/Elev= 30
9777.098725.31249780.078724.08679792.746724.34279805.415722.86879817.975 717.197
9834.446713.54359855.192705.98879891.065687.21889905.927677.74749926.445663.2347
9937.301660.2529 9959.87655.95019971.224652.562610002.68652.186510013.21 654.558
10023.78655.0477 10034.5651.362910045.22651.706810055.94657.289410066.65667.4419
10077.37674.560110088.09  683.3810162.94 754.96610183.96 778.36210204.65799.7318
10225.28816.352510255.64842.433310265.75848.741510275.81858.405410293.32 857.806
#Mann= 3 , 0 , 0
9777.098    0.12       09777.098    0.12       010293.32    0.12       0
#XS Ineff= 2 , 0
       0                               0
Bank Sta=9777.098,10293.32
Exp/Cntr=0.3,0.1

Type RM Length L Ch R = 1 ,31909.71,245.668200,245.668200,245.668200
XS GIS Cut Line= 6
476356.118477886797433.717271342476216.518020179797124.417111294
476193.674985538797048.891084976476184.459051202797004.255150101
476177.348442605796943.905280936476176.845349407  796913.4027171
#Sta/Elev= 30
9720.735 713.9029730.268708.53389741.272703.20589752.276702.51849774.285689.2039
9785.289683.8221 9819.55679.58789851.314674.54049862.318 670.8489873.322669.9472
9895.331663.2231 9972.36651.86989983.364648.29129994.368647.864910016.33648.1048
 10021.8649.913910027.19652.539710037.96663.926610048.73677.348810064.98694.3033
10080.56711.500510122.38746.709710143.03760.857110163.45766.790410193.96766.3983
10204.02 763.29710214.09 761.71910234.23761.8765 10244.3762.991310275.91770.6399
#Mann= 3 , 0 , 0
9720.735    0.12       09720.735    0.12       010275.91    0.12       0
#XS Ineff= 2 , 0
       0                               0
Bank Sta=9720.735,10275.91
Exp/Cntr=0.3,0.1

Type RM Length L Ch R = 1 ,31664.04,245.668200,245.668200,245.668200
XS GIS Cut Line= 6
476521.071398212797392.831504772476486.677764989797214.467340753
476477.957923307797128.061697569476468.690761555796919.058857271
476472.650683163796807.746494277476481.349341183796730.700322039
#Sta/Elev= 30
9730.455702.67879759.843698.75119779.341692.45789820.223688.75239840.583681.1465
9871.018663.22169881.163660.36989951.856658.9353 9961.92656.35399971.983651.1061
9992.046646.959510012.08646.445710032.12 648.45510042.14656.962310062.17680.4677
 10082.2707.467410102.23722.504610152.26738.326210182.27755.693810192.28766.2152
10212.29780.881710222.29 783.10310232.29783.197710262.29774.904910282.32772.0118
10312.37779.704710352.59780.961610372.71778.994810382.78780.527410397.17 785.718
#Mann= 3 , 0 , 0
9730.455    0.12       09730.455    0.12       010397.17    0.12       0
#XS Ineff= 2 , 0
       0                               0
Bank Sta=9730.455,10397.17
Exp/Cntr=0.3,0.1

Type RM Length L Ch R = 1 ,31418.37,245.668100,245.668100,245.668100
XS GIS Cut Line= 6
476735.504444351797339.681433521476723.177032487797113.153164587
476721.155580462796910.510722711476726.877540593796808.466911723
476735.306731298 796727.98345731 476749.08019495 796638.58412993
#Sta/Elev= 30
9774.136711.5207 9788.84707.58459798.855702.45439818.885697.26219838.915683.7142
 9848.93683.68469878.976667.34839899.006659.80339929.051656.62019959.096651.1057
9979.127 645.4779999.151645.342210029.16646.552410039.17651.782810079.18685.9787
10089.19698.1814 10139.2746.3768 10159.2761.4899 10169.2764.9144 10179.2760.9811
 10199.2746.417610229.24720.730310239.25713.716610249.27 716.59210305.89757.0431
10319.43763.672310329.49771.556210339.54774.247210369.71793.470410477.27839.1653
#Mann= 3 , 0 , 0
9774.136  0.0588       09774.136  0.0588       010477.27  0.0588       0
#XS Ineff= 2 , 0
       0                               0
Bank Sta=9774.136,10477.27
Exp/Cntr=0.3,0.1

Type RM Length L Ch R = 1 , 31172.7,245.668200,245.668200,245.668200
XS GIS Cut Line= 6
476957.021354473797353.730085327 476968.53516131797274.043280399
476968.836737193796984.762752052476973.823688326796892.268279996
476993.117259528796740.836635102477025.705238649796589.039345992
#Sta/Elev= 30
9749.129707.60649768.204 697.4349778.359696.83919798.622691.25019848.776667.5472
9868.784662.65799948.802655.88759988.807 643.4689998.809 643.43810018.81643.8832
10038.81649.169310048.81654.453710078.81665.295510088.81671.742110108.81689.9541
10138.84713.238910168.89732.534810198.93755.233610208.94759.374310222.89769.1852
10259.21788.140410279.32801.7457 10309.6826.065410360.16858.141310380.51864.8053
10411.07 870.85810441.64882.064210472.37885.239910492.95892.601510519.67897.0691
#Mann= 3 , 0 , 0
9749.129    0.12       09749.129    0.12       010519.67    0.12       0
#XS Ineff= 2 , 0
       0                               0
Bank Sta=9749.129,10519.67
Exp/Cntr=0.3,0.1

Type RM Length L Ch R = 1 ,30927.04,245.668200,245.668200,245.668200
XS GIS Cut Line= 6
477014.195893967797440.766668388477129.518049981 797328.50339209
477191.128455278797240.317357781477211.601334694797168.857635919
477228.058557277796975.773981548477305.191304812796729.161807181
#Sta/Elev= 30
9590.257719.58389671.828710.2335 9687.33703.55639701.179700.08449742.292 680.818
9791.134662.28949806.921658.26119864.866657.30549907.045652.58459927.472653.6329
9947.646649.16929957.677648.82469977.702642.620810017.71642.868510027.72645.0336
10037.73652.8188 10057.8657.5587 10098.2686.248710108.37690.707510139.03697.6976
10149.36702.341210221.65749.0768 10263.6769.147810274.09773.709410284.61773.7124
10295.21770.948710305.82772.240710316.42777.574210358.86 809.95110386.53826.3342
#Mann= 3 , 0 , 0
9590.257    0.12       09590.257    0.12       010386.53    0.12       0
#XS Ineff= 2 , 0
       0                               0
Bank Sta=9590.257,10386.53
Exp/Cntr=0.3,0.1