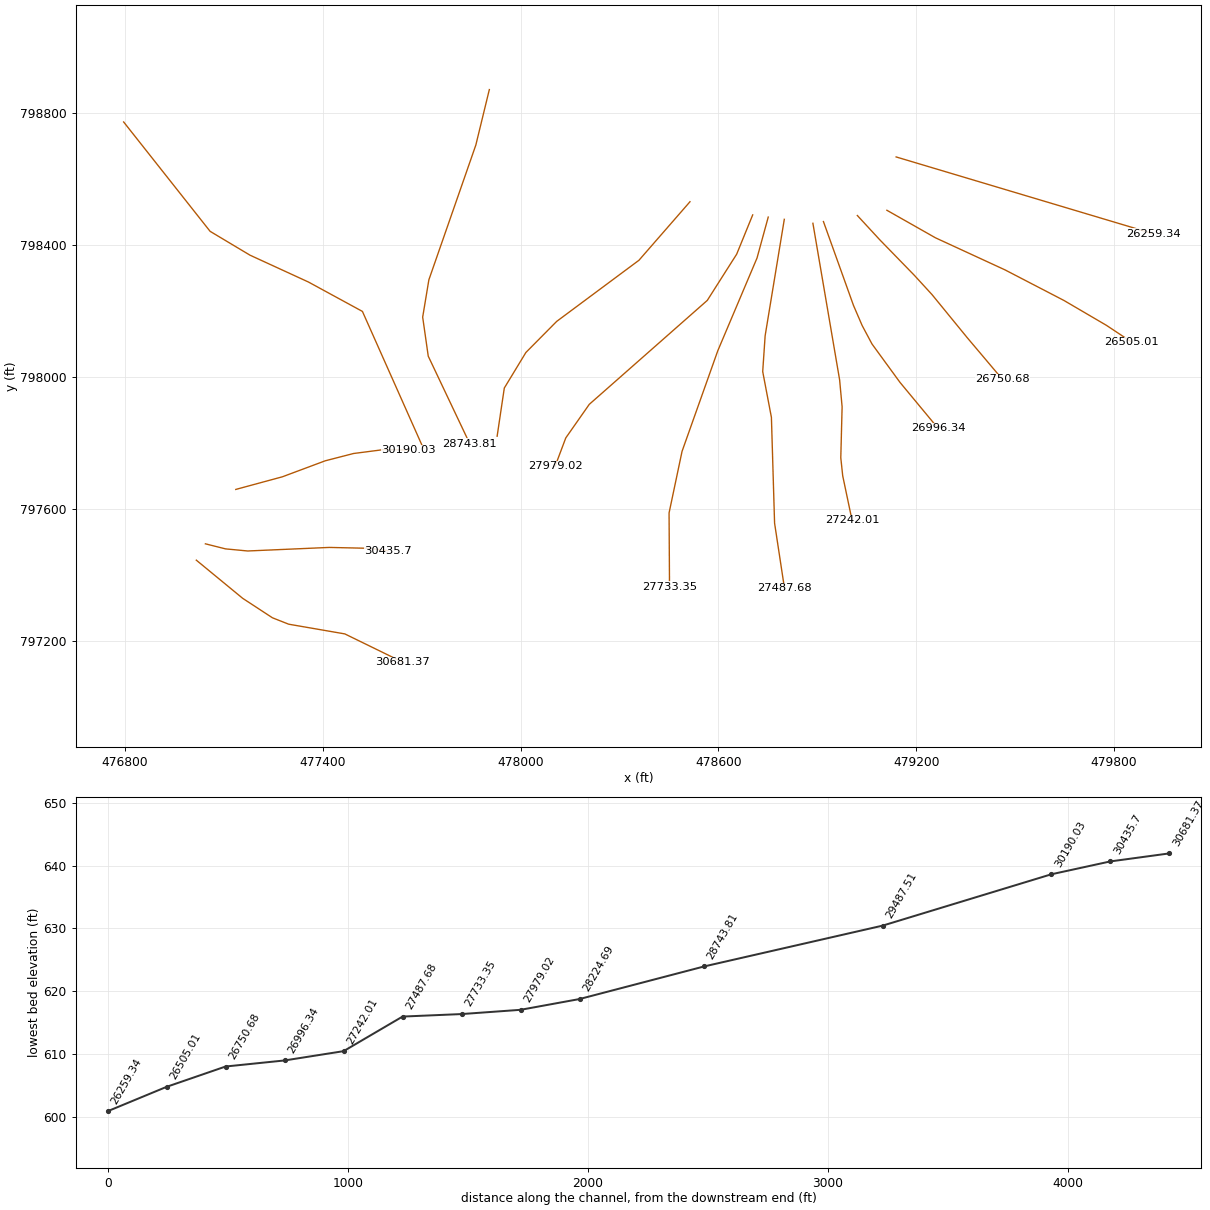
HEC-RAS study 5528_ras.prj: 5528

--- 5528_ras.g01 (geometry) --- (continued)

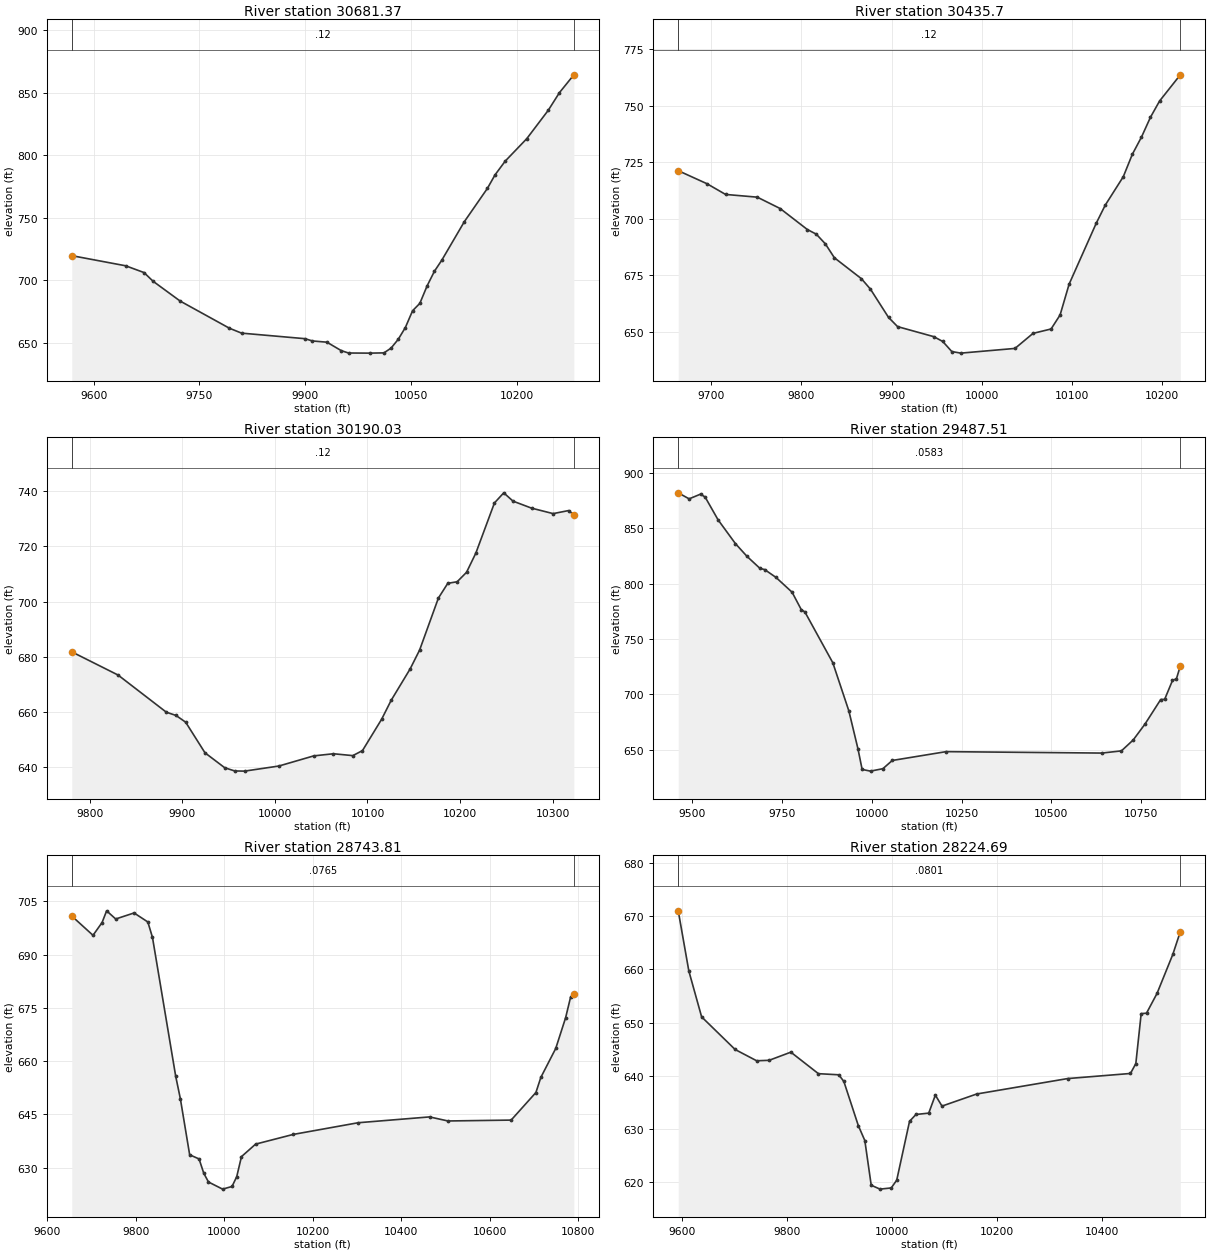
Type RM Length L Ch R = 1 ,30681.37,245.668200,245.668200,245.668200
XS GIS Cut Line= 6
477016.500208061797444.893798101477157.259294878797329.092756286
477247.461031275797270.090342971477296.741284357797250.661512853
477466.929888665 797221.23153867477642.257396413797135.623858794
#Sta/Elev= 30
 9568.98719.7925 9645.39711.7051 9671.47706.28799684.286 699.3579722.735683.5205
9792.661661.80829809.843657.90969899.763653.47329910.353 651.6639930.887650.6745
 9951.36 643.8899961.596642.03289991.767641.938510011.81642.137510021.87645.9497
   10032652.941710042.13662.360210052.37675.779710062.71681.710410073.04695.7103
10083.38707.332510093.93716.268610125.75746.894810158.43773.450210169.38784.3497
 10183.8795.317210214.33813.212210244.86835.914110260.71850.000710281.13864.2265
#Mann= 3 , 0 , 0
 9568.98    0.12       0 9568.98    0.12       010281.13    0.12       0
#XS Ineff= 2 , 0
       0                               0
Bank Sta=9568.98,10281.13
Exp/Cntr=0.3,0.1

Type RM Length L Ch R = 1 , 30435.7,245.668200,245.668200,245.668200
XS GIS Cut Line= 6
477044.153004441797494.421194624477105.082590655797479.096309038
477172.533849824797472.708267893477419.547411308797483.500388276
477537.877515633 797480.89116486477597.771435019797473.704892011
#Sta/Elev= 30
9663.529721.35619695.439 715.5769716.013710.84599751.171709.64239776.603704.5977
9806.646695.33919816.647693.26359826.648688.99979836.649682.84419866.665673.5696
9876.683668.94459896.719656.45439906.737652.3882 9946.81647.95799956.828645.8167
9966.846641.36289976.864640.663910036.93642.745810056.93649.404410076.93651.3416
10086.93657.545510096.93671.175910126.96698.078310136.97706.102710156.99718.6831
10167.03728.605510177.09736.148410187.14744.9913 10197.2752.146210220.22763.7451
#Mann= 3 , 0 , 0
9663.529    0.12       09663.529    0.12       010220.22    0.12       0
#XS Ineff= 2 , 0
       0                               0
Bank Sta=9663.529,10220.22
Exp/Cntr=0.3,0.1

Type RM Length L Ch R = 1 ,30190.03,702.521200,702.521200,702.521200
XS GIS Cut Line= 6
477136.247042942 797659.36574122477277.517197311797697.661379459
477407.694876058797746.253134616477493.361853306797768.323953907
477586.343740311797780.367059708 477660.59480087797778.612478353
#Sta/Elev= 30
9780.776681.80299830.754673.40669882.886659.94559893.313658.7773 9903.74656.3323
9924.593645.25189945.913639.83729956.607638.68559967.301638.614410004.36640.4613
   10042 644.134 10063.3644.905610084.19644.2294 10094.6646.0374 10115.3657.3969
10125.56664.232710146.09675.631410156.33682.472410176.59701.278510186.72706.6148
10196.86707.187210206.97710.607510217.02717.5612 10237.1735.724610247.14739.3838
10257.14736.375310277.14733.844410300.45731.857210317.21 732.96510322.82731.3518
#Mann= 3 , 0 , 0
9780.776    0.12       09780.776    0.12       010322.82    0.12       0
#XS Ineff= 2 , 0
       0                               0
Bank Sta=9780.776,10322.82
Exp/Cntr=0.3,0.1

Type RM Length L Ch R = 1 ,29487.51,743.696900,743.696900,743.696900
XS GIS Cut Line= 6
476796.171138078798773.770515531477058.391509086798442.081533313
477179.394389272798369.771710187477356.396302134798288.459243447
477520.319892943798199.221353754477704.609246761 797785.11233525
#Sta/Elev= 30
9460.483882.19819490.844876.75129522.654881.02199535.401878.36049571.467857.7606
9619.841 836.233 9652.09824.69789688.371813.77889701.118812.80279732.713805.6992
9777.603792.29529803.098776.60179813.337774.4046 9891.02728.51129935.766684.8952
9961.075650.66749972.751631.95299996.074630.439310030.57632.644710056.67640.0838
10206.68648.068710640.24646.775910694.97648.749510727.81658.618210760.65673.0128
10804.43695.217510815.37695.337310837.26712.479210848.21 713.98810859.03725.5265
#Mann= 3 , 0 , 0
9460.483  0.0583       09460.483  0.0583       010859.03  0.0583       0
#XS Ineff= 2 , 0
       0                               0
Bank Sta=9460.483,10859.03
Exp/Cntr=0.3,0.1

Type RM Length L Ch R = 1 ,28743.81,519.127400,519.127400,519.127400
XS GIS Cut Line= 6
477905.194854665798871.987430906477864.248208234798703.755333073
477721.844609037798295.134494161477703.037208095798181.885326167
477719.921062795798063.534012646477845.642864601797798.435311596
#Sta/Elev= 30
9655.477700.86029703.464695.4276 9723.99699.03119734.254702.32559754.797700.0274
9796.295701.72659827.419699.18389837.906694.83419890.421  655.719900.924 649.403
9921.947633.61119943.218632.43819953.854628.4042 9964.49625.94149996.396623.9378
10017.69624.684610028.35627.451310039.01633.086210071.01636.614510156.03639.3451
10302.73642.636510464.18644.279210505.81643.1347 10648.6643.383310704.58651.1535
10715.78655.424110749.37 663.55610771.76672.232710782.96678.027210790.31679.0222
#Mann= 3 , 0 , 0
9655.477  0.0765       09655.477  0.0765       010790.31  0.0765       0
#XS Ineff= 2 , 0
       0                               0
Bank Sta=9655.477,10790.31
Exp/Cntr=0.3,0.1

Type RM Length L Ch R = 1 ,28224.69,245.668200,245.668200,245.668200
XS GIS Cut Line= 6
478513.659933967798531.851857322478358.903353874798354.326141478
478109.314045128798168.851411798478016.050079624798074.682847758
477950.583321778 797966.88171599477928.841267863797820.807578353
#Sta/Elev= 30
9593.477670.98869613.671659.6867 9637.99651.08359701.754644.95899742.779642.8395
9766.493642.92729807.859644.4565 9860.35 640.4199899.126640.20779908.782638.9542
9936.308630.66999948.701627.86819960.866619.47719977.611618.7453    9999  618.97
10009.44620.430510033.81631.471110045.99632.757810070.36633.011910082.94636.3932
10095.63634.332410161.68636.602810334.61639.497610454.42640.456110464.62642.3144
10474.81651.685610484.98651.7771   10505 655.48710535.04662.808810549.31667.0734
#Mann= 3 , 0 , 0
9593.477  0.0801       09593.477  0.0801       010549.31  0.0801       0
#XS Ineff= 2 , 0
       09789.235                       0
Bank Sta=9593.477,10549.31
Exp/Cntr=0.3,0.1

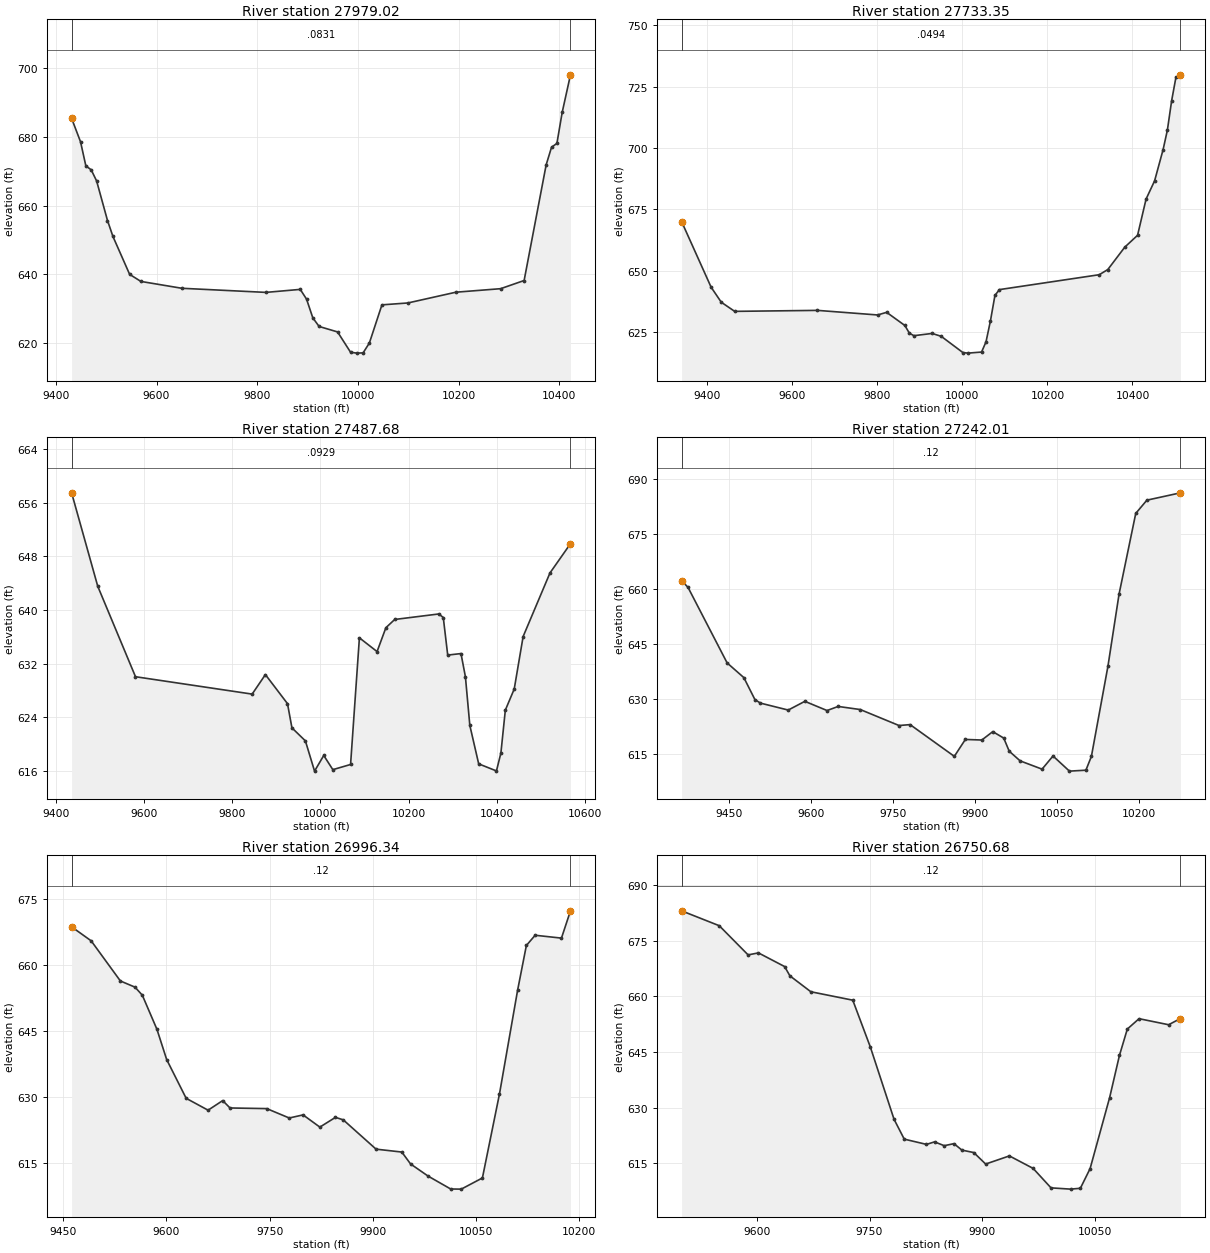
Type RM Length L Ch R = 1 ,27979.02,245.668200,245.668200,245.668200
XS GIS Cut Line= 6
478703.859562221 798491.87453778478655.341747681798372.924676417
 478566.17908811798232.647877372478208.212674419797917.335972687
478137.005179296797815.544304777478104.456628572797729.044597074
#Sta/Elev= 30
9431.354685.37169449.111678.53389459.634671.5412 9470.22670.3881 9481.02667.1502
 9502.62655.6349 9513.42650.9905  9546.6639.9583 9568.99637.89719650.292635.9044
9817.362634.70849885.421635.58229897.908632.75599910.396627.29129922.884624.7921
9959.589623.19439985.323  617.299997.811617.028510010.26617.102610022.72619.9804
10047.63 631.08110099.15631.630310194.42634.760110283.36635.786610330.03638.1672
10373.81671.848110384.48 676.96910395.14678.078310405.58 687.08710422.08698.0394
#Mann= 3 , 0 , 0
9431.354  0.0831       09431.354  0.0831       010422.08  0.0831       0
#XS Ineff= 2 , 0
       0                               0
Bank Sta=9431.354,10422.08
Exp/Cntr=0.3,0.1

Type RM Length L Ch R = 1 ,27733.35,245.668200,245.668200,245.668200
XS GIS Cut Line= 6
478751.017665592798485.324801208478717.015834577798361.237000039
478598.028887572798079.985843048478489.595617992797774.742468138
478450.243064348797588.085736238478451.619030444797364.374211822
#Sta/Elev= 30
9339.456 669.9989408.894643.22999432.758637.11339464.303633.38189659.106633.7831
9800.422631.91449821.818632.9845 9864.61627.62149875.308624.46939886.006 623.464
9928.799624.38119950.195623.2013   10001616.597610013.06616.351710045.06616.7895
10055.54620.976310066.02629.594110076.51639.890510086.99642.253610321.92648.3289
10341.99650.433610382.01659.582110412.01664.407910432.04679.184910452.09686.6215
10472.13 699.38610482.15707.307910492.17719.294710502.22728.792710512.93729.8383
#Mann= 3 , 0 , 0
9339.456  0.0494       09339.456  0.0494       010512.93  0.0494       0
#XS Ineff= 2 , 0
       0                               0
Bank Sta=9339.456,10512.93
Exp/Cntr=0.3,0.1

Type RM Length L Ch R = 1 ,27487.68,245.668100,245.668100,245.668100
XS GIS Cut Line= 6
478799.736899349 798478.55824096478741.615886375798125.596465516
478734.230907155798016.779656591478760.634685889797877.747030071
478770.222605295797557.155067564 478800.25728555797359.435357113
#Sta/Elev= 30
9436.279657.49839495.504643.54759581.023630.04569845.304 627.4519875.313 630.364
9925.379626.02659935.419622.41469965.943620.46459986.683615.9528 10007.5 618.291
 10028.1616.172710068.29 616.94410088.29635.8514 10128.3 633.799 10148.3637.3638
 10168.3638.592310268.33 639.41610278.33638.878310288.35 633.27610318.43633.5021
10328.45630.047610338.48622.768210358.53 617.03810398.77 615.98110408.83618.6477
 10418.9625.058610439.04628.209110459.23636.048910520.03645.536810566.48649.9047
#Mann= 3 , 0 , 0
9436.279  0.0929       09436.279  0.0929       010566.48  0.0929       0
#XS Ineff= 2 , 0
       0                10220.35       0
Bank Sta=9436.279,10566.48
Exp/Cntr=0.3,0.1

Type RM Length L Ch R = 1 ,27242.01,245.668200,245.668200,245.668200
XS GIS Cut Line= 6
478886.463511194798466.512878181478967.479693501797991.590899081
478975.021269965797909.876254046478971.029903166797755.265609896
478976.840792237797700.714881612479005.269904878797565.324309746
#Sta/Elev= 30
9363.286662.4013 9375.04660.52619446.508639.94039477.073635.93659497.353629.9357
9507.493628.98169558.192627.09299588.611629.4725 9629.17626.9619 9649.45628.0759
9689.961627.23099760.776622.87629781.009623.12659861.857614.47339881.991619.0812
9912.101618.92389932.133621.21189952.163  619.459962.178615.88089982.207613.2347
10022.24610.984910042.25614.568810072.25610.445110102.37610.698910112.43614.4601
10142.66639.040810162.99658.709310193.48680.697710213.86684.310810275.25686.3112
#Mann= 3 , 0 , 0
9363.286    0.12       09363.286    0.12       010275.25    0.12       0
#XS Ineff= 2 , 0
       0                               0
Bank Sta=9363.286,10275.25
Exp/Cntr=0.3,0.1

Type RM Length L Ch R = 1 ,26996.34,245.668200,245.668200,245.668200
XS GIS Cut Line= 6
478918.390923069798471.759610713479009.502298067798217.490109602
 479035.74608797798156.539035928479065.642811018798100.474846037
479150.351939893797984.280870573479266.000844467797844.723731716
#Sta/Elev= 30
9462.082668.71859490.508665.53079532.999656.38479554.244654.97659564.866653.1436
9586.112645.37949600.255638.49169628.602629.6529 9660.47626.94859681.715629.1361
9692.338627.45369745.782627.30779778.444625.17039798.544625.87579822.954623.0945
 9845.62625.31169856.953624.74989904.645618.0716 9942.11617.4097 9954.77614.7057
9980.312611.930510013.12608.9953 10028.5608.964710059.25611.508710084.01630.6096
10110.34654.223210123.14  664.47 10135.9666.801510174.15666.148510187.26672.3661
#Mann= 3 , 0 , 0
9462.082    0.12       09462.082    0.12       010187.26    0.12       0
#XS Ineff= 2 , 0
       0                               0
Bank Sta=9462.082,10187.26
Exp/Cntr=0.3,0.1

Type RM Length L Ch R = 1 ,26750.68,245.668200,245.668200,245.668200
XS GIS Cut Line= 6
479021.275504042798490.050202892479089.045838872798416.663517706
479194.559507216798308.201950754479247.635221547798250.279579164
479354.761680738 798119.22198951 479461.11033911797993.317055481
#Sta/Elev= 30
9499.944683.09279550.066679.07439588.425671.20249602.171 671.7429637.071668.0506
9644.025665.55859671.928661.25659727.733658.98199751.168646.31299782.638626.8559
9796.226621.4892 9825.83620.07129836.549620.75179849.465619.71829862.381  620.27
9872.969 618.527 9888.77617.86849904.571614.76889936.173616.96259967.775613.5925
9991.537608.341310017.51607.999710030.61608.225810043.55613.531210069.58632.7144
 10082.6644.0622 10093.1651.191910108.72653.989610148.08652.357310163.83654.0387
#Mann= 3 , 0 , 0
9499.944    0.12       09499.944    0.12       010163.83    0.12       0
#XS Ineff= 2 , 0
       0                               0
Bank Sta=9499.944,10163.83
Exp/Cntr=0.3,0.1

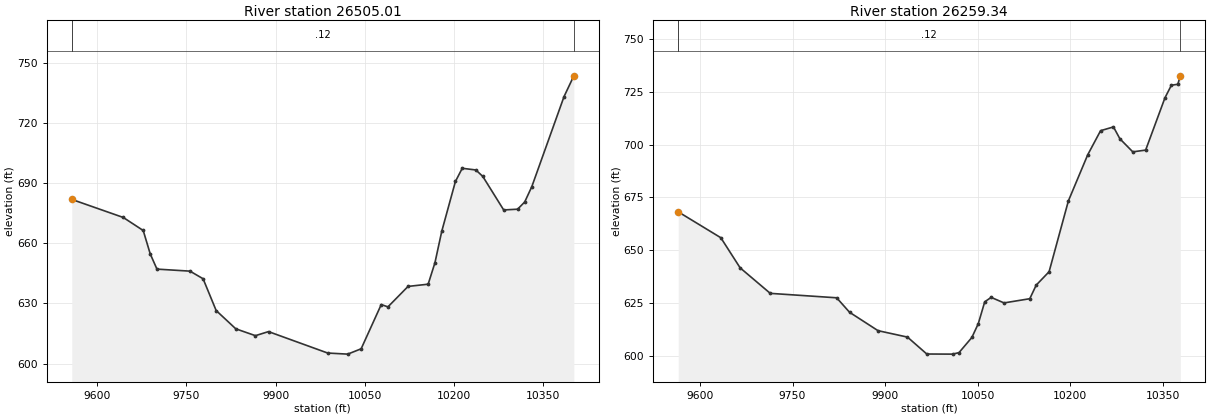
Type RM Length L Ch R = 1 ,26505.01,245.668200,245.668200,245.668200
XS GIS Cut Line= 6
479110.824592249798505.970040808479258.149582603798422.451878105
479468.910965128798325.249656848479647.752906825798232.460601152
479776.352367234798157.155787925  479853.9618671798105.727178249
#Sta/Elev= 30
9556.914681.84949643.563672.85889677.176666.36239689.082654.63129700.333 647.117
9755.947646.10929777.971 642.3179799.996626.47749833.033617.3745 9866.07613.9611
9888.094615.98469987.719605.306710021.49604.764210044.05607.422210077.89629.4609
10089.17628.310910123.01638.499210156.85639.605810168.28  650.2910179.77665.9917
10202.75690.779310214.24697.355510237.21696.510310248.84693.292710283.99676.5947
10307.42676.973710319.36680.551610331.33688.190710385.64733.097710402.11743.4192
#Mann= 3 , 0 , 0
9556.914    0.12       09556.914    0.12       010402.11    0.12       0
#XS Ineff= 2 , 0
       0                               0
Bank Sta=9556.914,10402.11
Exp/Cntr=0.3,0.1

Type RM Length L Ch R = 1 ,26259.34,79.587500,79.587500,79.587500
XS GIS Cut Line= 2
479138.851384025798667.705779633479918.861153781798434.715848386
#Sta/Elev= 30
9564.651668.16399633.688655.92119664.997641.68399713.864629.61269821.546627.5141
9842.419620.67349888.564611.97269936.348608.92739967.658600.9312 10009.4600.8766
10019.84601.576210040.71608.741510051.15615.279910061.59 625.61210072.02627.7113
 10092.9625.093110134.64627.080810145.08633.517510165.95639.843410197.26673.3618
10228.57695.132510249.45706.539310270.32708.318810280.76702.706510301.63 696.531
 10322.5697.360110353.81722.083610364.25 728.03510374.68728.492310378.71732.4809
#Mann= 3 , 0 , 0
9564.651    0.12       09564.651    0.12       010378.71    0.12       0
#XS Ineff= 2 , 0
       0                               0
Bank Sta=9564.651,10378.71
Exp/Cntr=0.3,0.1