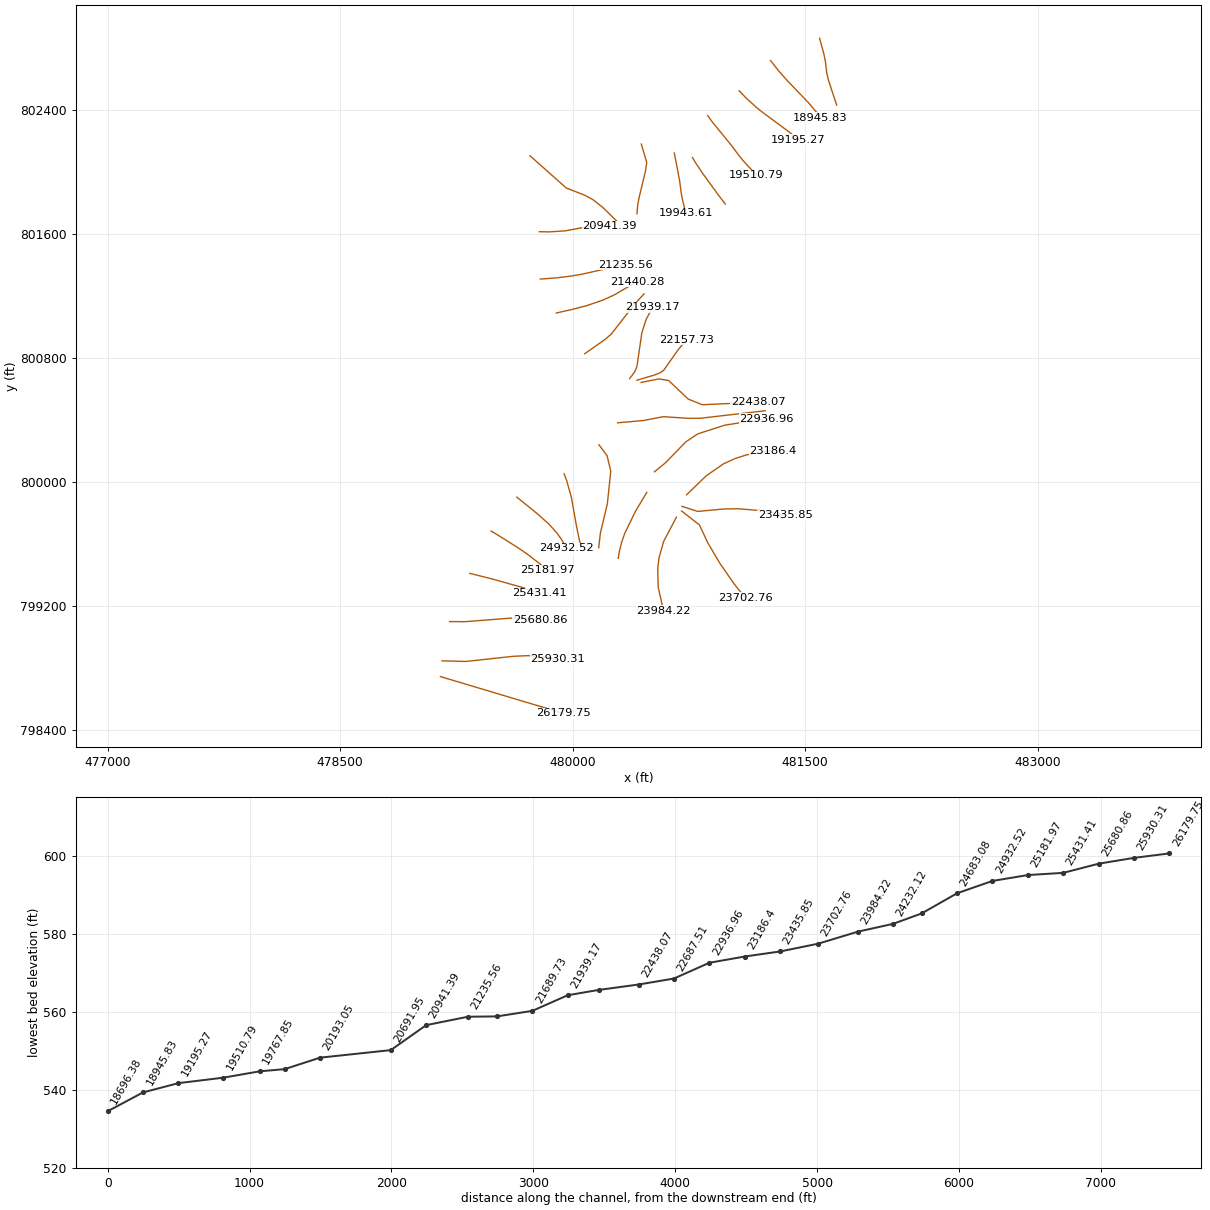
HEC-RAS study 5528_ras.prj: 5528

--- 5528_ras.g01 (geometry) --- (continued)

Type RM Length L Ch R = 3 , 26219.2,,,
BEGIN DESCRIPTION:
END DESCRIPTION:
Bridge Culvert--1,0,-1,-1, 0
Deck Dist Width WeirC Skew NumUp NumDn MinLoCord MaxHiCord MaxSubmerge Is_Ogee
26.834450,25.918600,2.6,0, 60, 60, , , 0.95, 0, 0,0,,
 9558.91 9566.96 9587.85 9608.74 9619.18 9629.63 9640.08 9660.97 9671.41 9681.86
 9692.30 9713.19 9734.08 9744.53 9751.06 9765.42 9785.68 9796.76 9807.20 9820.29
 9838.54 9848.98 9880.74 9924.05 9924.0510075.9510075.9510078.2310078.7810089.23
10110.1210120.5610131.0110141.4510151.9010162.3410166.4410172.7910183.2410193.68
10204.1310214.5710225.0210235.4610245.9110266.8010270.2810277.2410287.6910298.13
10304.9010308.5810319.0310329.4710339.9210350.3610360.8110371.2510374.1310382.21
  663.82  662.11  656.16  649.71  647.55  644.56  641.99  636.07  634.01  632.20
  630.73  628.45  626.78  626.07  625.82  625.73  623.55  623.45  624.18  625.43
  626.26  626.13  624.24  624.14  624.14  623.79  623.79  623.78  623.96  624.45
  624.67  626.74  627.52  634.84  644.45  651.33  652.22  653.21  656.55  663.94
  673.41  680.58  688.32  695.36  701.93  715.67  716.59  718.04  718.73  719.86
  720.10  719.45  718.39  715.70  714.02  717.70  722.95  723.80  725.88  733.04
 -336.18 -337.89 -343.84 -350.29 -352.45 -355.44 -358.01 -363.93 -365.99 -367.80
 -369.27 -371.55 -373.22 -373.93 -374.18 -374.27 -376.45 -376.55 -375.82 -374.57
 -373.74 -373.87 -375.76 -375.86  619.64  619.29 -376.21 -376.22 -376.04 -375.55
 -375.33 -373.26 -372.48 -365.16 -355.55 -348.67 -347.78 -346.79 -343.45 -336.06
 -326.59 -319.42 -311.68 -304.64 -298.07 -284.33 -283.41 -281.96 -281.27 -280.14
 -279.90 -280.55 -281.61 -284.30 -285.98 -282.30 -277.05 -276.20 -274.12 -266.96
 9558.91 9566.96 9587.85 9608.74 9619.18 9629.63 9640.08 9660.97 9671.41 9681.86
 9692.30 9713.19 9734.08 9744.53 9751.06 9765.42 9785.68 9796.76 9807.20 9820.29
 9838.54 9848.98 9880.74 9924.05 9924.0510075.9510075.9510078.2310078.7810089.23
10110.1210120.5610131.0110141.4510151.9010162.3410166.4410172.7910183.2410193.68
10204.1310214.5710225.0210235.4610245.9110266.8010270.2810277.2410287.6910298.13
10304.9010308.5810319.0310329.4710339.9210350.3610360.8110371.2510374.1310382.21
  663.82  662.11  656.16  649.71  647.55  644.56  641.99  636.07  634.01  632.20
  630.73  628.45  626.78  626.07  625.82  625.73  623.55  623.45  624.18  625.43
  626.26  626.13  624.24  624.14  624.14  623.79  623.79  623.78  623.96  624.45
  624.67  626.74  627.52  634.84  644.45  651.33  652.22  653.21  656.55  663.94
  673.41  680.58  688.32  695.36  701.93  715.67  716.59  718.04  718.73  719.86
  720.10  719.45  718.39  715.70  714.02  717.70  722.95  723.80  725.88  733.04
 -336.18 -337.89 -343.84 -350.29 -352.45 -355.44 -358.01 -363.93 -365.99 -367.80
 -369.27 -371.55 -373.22 -373.93 -374.18 -374.27 -376.45 -376.55 -375.82 -374.57
 -373.74 -373.87 -375.76 -375.86  619.64  619.29 -376.21 -376.22 -376.04 -375.55
 -375.33 -373.26 -372.48 -365.16 -355.55 -348.67 -347.78 -346.79 -343.45 -336.06
 -326.59 -319.42 -311.68 -304.64 -298.07 -284.33 -283.41 -281.96 -281.27 -280.14
 -279.90 -280.55 -281.61 -284.30 -285.98 -282.30 -277.05 -276.20 -274.12 -266.96
Pier Skew, UpSta & Num, DnSta & Num=  ,10000.00, 2 ,10000.00, 2 , 0 , 0 , 0 ,,
    4.00    4.00
 -376.04  623.96
    4.00    4.00
 -376.04  623.96
BR Coef=-1 , 0 , 0 ,, 0 ,,,0.8,0,1,0,
WSPro=,,,, 1 ,,,, 0 ,,,, 0 ,,,,-1 ,-1 ,-1 , 0 , 0 , 0 , 0 , 0
BC Design=,, 0 ,, 0 ,,,,,,

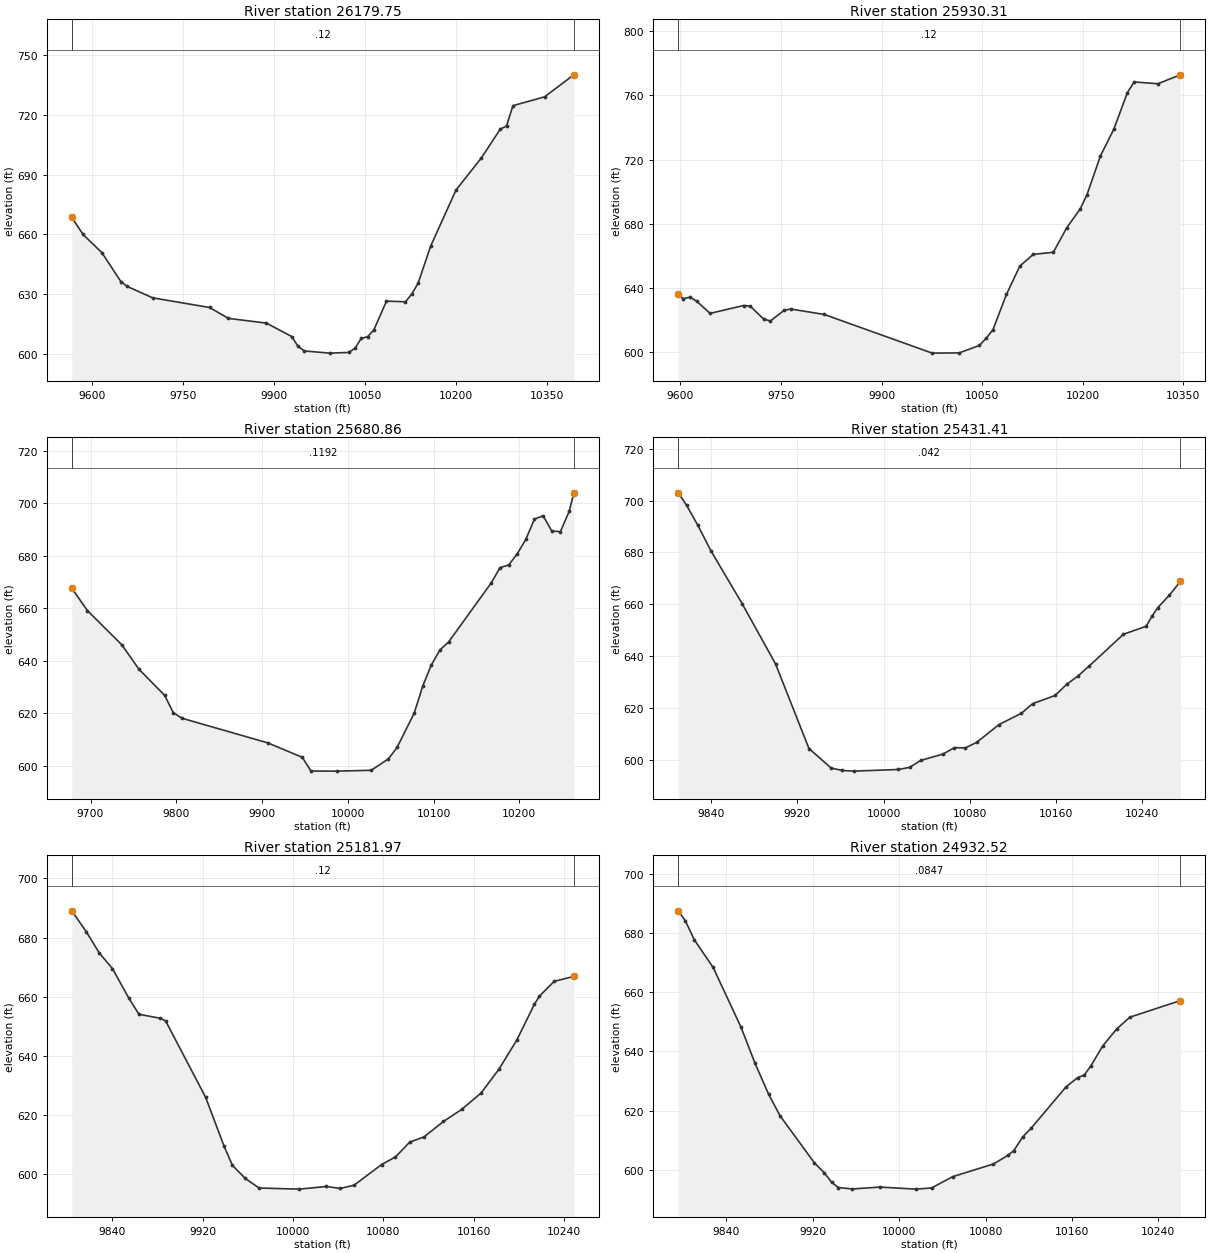
Type RM Length L Ch R = 1 ,26179.75,249.445700,249.445700,249.445700
XS GIS Cut Line= 2
479147.083893599798746.641018477479941.430598226798509.368626164
#Sta/Elev= 30
9565.816668.51069584.515659.97969615.824 650.7769647.134636.30219657.571633.9519
9699.317628.27659793.246623.43519824.556617.97739887.176615.61889928.922608.9129
9939.358604.01989949.795601.68449991.541600.591210022.85600.931710033.29602.9348
10043.72607.947410054.16608.8106 10064.6612.221310085.47626.618310116.78626.2983
10127.22630.163610137.65635.568210158.53654.266810200.27682.238210242.02698.2365
10273.33712.701610283.77714.3193 10294.2724.441210346.39728.863510394.84739.8941
#Mann= 3 , 0 , 0
9565.816    0.12       09565.816    0.12       010394.84    0.12       0
#XS Ineff= 2 , 0
       0                               0
Bank Sta=9565.816,10394.84
Exp/Cntr=0.3,0.1

Type RM Length L Ch R = 1 ,25930.31,249.445800,249.445800,249.445800
XS GIS Cut Line= 6
479157.668113179 798848.12500631479311.879093305798844.383672843
479619.151744784 798877.72099391479713.282779259798881.864485826
479830.957789498798872.481416349479902.300718919798857.395583028
#Sta/Elev= 30
9596.756636.0229 9604.12633.36719614.164634.27959624.207631.80269644.261624.2253
9694.273629.12269704.276628.67329724.282620.59639734.286619.49759754.301626.0168
9764.333626.94379814.492623.55399975.559599.450410015.88599.600810046.08604.2409
10056.15608.784610066.19614.043410086.24635.985710106.29653.696610126.29660.9993
 10156.3662.278810176.32677.624810196.33689.320210206.34698.007410226.47722.2947
10246.59739.059610266.71761.798610276.82768.441310312.22 767.30510345.67772.8635
#Mann= 3 , 0 , 0
9596.756    0.12       09596.756    0.12       010345.67    0.12       0
#XS Ineff= 2 , 0
       09768.131                       0
Bank Sta=9596.756,10345.67
Exp/Cntr=0.3,0.1

Type RM Length L Ch R = 1 ,25680.86,249.445700,249.445700,249.445700
XS GIS Cut Line= 6
 479206.68329682799101.722961879479303.585411257799100.759817213
479593.871415237799123.379232521479682.445965098799125.569297266
479733.291564918799122.609178178479790.374308009799114.430909675
#Sta/Elev= 30
9678.153667.62099696.471659.07249736.473646.07799756.474 636.7719786.491626.7932
9796.505620.22379806.519618.10799906.792608.70389946.962603.19769957.004597.9829
9987.132597.954410027.27 598.27810047.34602.628710057.37606.9549 10077.4620.0606
 10087.4630.4396 10097.4638.402810107.41644.132810117.41647.106110167.44669.7723
10177.46675.476410187.48676.471110197.49 680.71310207.52686.2452 10217.6693.9691
10227.68695.206910237.76689.408610247.83689.172810258.01696.859410263.49703.9578
#Mann= 3 , 0 , 0
9678.153  0.1192       09678.153  0.1192       010263.49  0.1192       0
#XS Ineff= 2 , 0
       0                               0
Bank Sta=9678.153,10263.49
Exp/Cntr=0.3,0.1

Type RM Length L Ch R = 1 ,25431.41,249.445800,249.445800,249.445800
XS GIS Cut Line= 6
479337.409322108799412.380167644479482.520502689799376.046800249
479522.793078768 799364.66174506479671.010378025799323.259776069
479759.967878854799293.077703096479784.235435849799282.749598868
#Sta/Elev= 30
9809.558702.96459817.383698.09969827.692690.46889839.944680.55169868.927660.1323
9899.853636.93199930.779 604.3319951.396596.78699961.725595.86959972.115595.6038
10013.67596.239610024.06597.040410034.44599.731410055.21602.205810065.59604.6383
10075.97604.593810086.35606.703210107.12613.583110127.89 617.93910138.27621.6362
 10159.1624.789210169.66629.034810180.22632.274910190.78636.179510222.46648.4076
10243.58651.499310248.83655.3167 10254.3658.680910265.17663.5349 10275.2668.7723
#Mann= 3 , 0 , 0
9809.558   0.042       09809.558   0.042       0 10275.2   0.042       0
#XS Ineff= 2 , 0
       0                               0
Bank Sta=9809.558,10275.2
Exp/Cntr=0.3,0.1

Type RM Length L Ch R = 1 ,25181.97,249.445700,249.445700,249.445700
XS GIS Cut Line= 6
 479473.88074113 799685.32300563479517.492699305799659.868689792
479653.161149773799574.206496153479712.781282072799532.680639632
479791.347529889799471.889670802479838.325708439 799432.53804605
#Sta/Elev= 30
9804.258689.06759817.132681.98699828.711674.7762 9840.29669.53059854.755659.5677
9863.629654.13169882.638652.75539887.271651.88989922.733626.04499938.898609.6569
9946.375 603.0889957.651598.68789970.016595.414510005.51  595.0410029.63595.9391
10041.82595.2652   10054596.368810078.38603.341610090.67605.915810103.31610.9252
10115.95612.692810133.09617.901310149.43622.027110166.53627.572710182.12635.5092
10197.93645.3476 10213.5657.441910218.05660.2586 10231.1665.250610248.48666.9124
#Mann= 3 , 0 , 0
9804.258    0.12       09804.258    0.12       010248.48    0.12       0
#XS Ineff= 2 , 0
       0                               0
Bank Sta=9804.258,10248.48
Exp/Cntr=0.3,0.1

Type RM Length L Ch R = 1 ,24932.52,249.445700,249.445700,249.445700
XS GIS Cut Line= 6
479639.911321441799904.457563441479772.058612004799797.267415074
479847.235382551799730.219965441479897.046905438799674.696005854
479924.310701432799637.274242514479961.799279896799574.525941962
#Sta/Elev= 30
9795.353687.48079801.905 684.1499810.366677.63369827.657668.37569853.409648.2754
9866.286636.16949879.162625.49429889.736618.23549921.484602.39759930.666599.0143
9937.358595.90419943.542594.07969956.419593.59179982.472594.230810015.11593.5334
10029.98593.924910049.51597.736210087.27602.022910101.07605.0215 10106.1606.5474
10114.39611.151810122.14614.0848 10154.4628.007810165.26631.184610171.38632.0436
10177.63 635.23110188.48641.889710201.74647.723810213.59651.573410260.32657.1773
#Mann= 3 , 0 , 0
9795.353  0.0847       09795.353  0.0847       010260.32  0.0847       0
#XS Ineff= 2 , 0
       0                               0
Bank Sta=9795.353,10260.32
Exp/Cntr=0.3,0.1

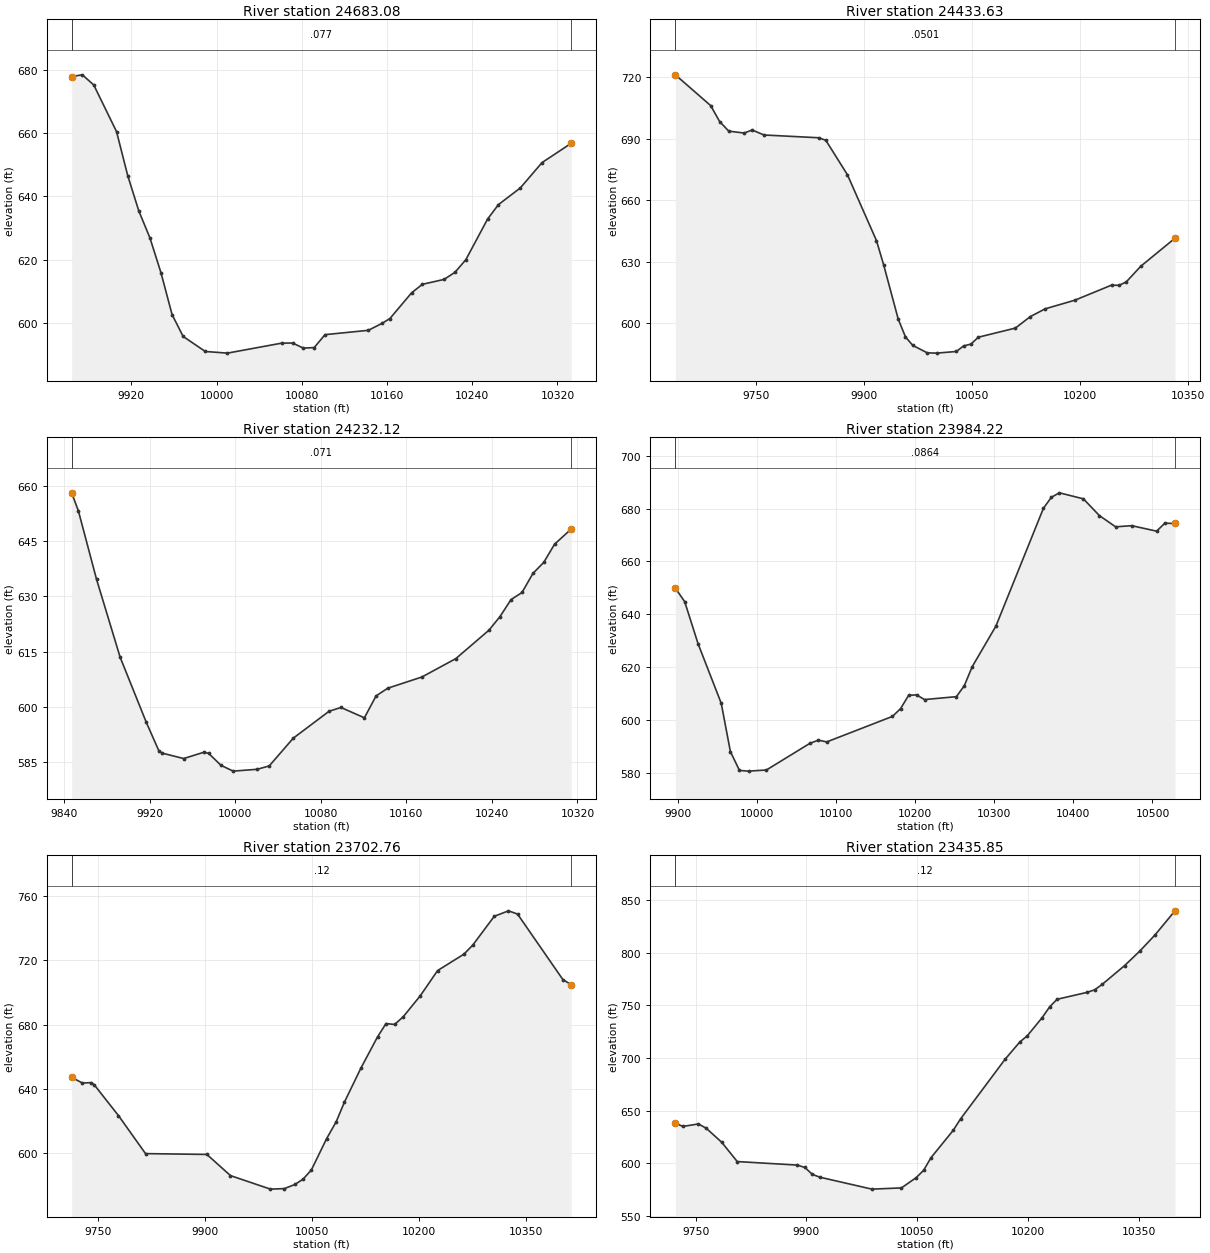
Type RM Length L Ch R = 1 ,24683.08,249.445800,249.445800,249.445800
XS GIS Cut Line= 6
479945.108915983800054.394145897479961.444444449800011.424021674
479992.640931954799899.534879011480023.749024783799722.592013957
480042.829143583799630.418140719480050.289709564799598.304349056
#Sta/Elev= 30
9864.024677.95469874.074678.48999884.772675.27789906.169660.50419916.675646.5575
9927.075635.38329937.475626.87629947.875615.81769958.275602.58769968.674595.6511
9989.474590.8947 10010.2590.373310061.22593.539410071.38593.571910081.53591.9609
10091.68592.136410101.84596.222410142.45597.593710155.29599.784110162.76601.3316
10183.06609.456710193.22612.164710213.57613.710710223.78615.963210233.99619.9501
10254.42632.829810264.63637.407210285.05642.648710305.51650.700210332.91656.8184
#Mann= 3 , 0 , 0
9864.024   0.077       09864.024   0.077       010332.91   0.077       0
#XS Ineff= 2 , 0
       0                               0
Bank Sta=9864.024,10332.91
Exp/Cntr=0.3,0.1

Type RM Length L Ch R = 1 ,24433.63,201.514200,201.514200,201.514200
XS GIS Cut Line= 6
480169.606066947800242.346237746480222.021236659800172.096326486
480245.891246053800072.414719047480224.076705994799861.893614606
480178.832321132 799671.45096764480168.251776708799577.789206941
#Sta/Elev= 30
9638.448721.30389687.441706.25489699.865698.47449712.527693.76439733.832692.8376
 9745.08694.30749761.413691.88429837.168690.52849847.178689.30519877.206672.4311
9917.462640.27159927.535628.30279947.683 601.8399957.756593.1362 9967.83588.9844
9987.977585.3433   10001585.205310028.31586.011610038.39588.726510048.56589.6203
10058.77  592.9810110.18597.441810130.84603.0371 10151.5606.856210192.82611.0954
10243.85 618.48710253.96618.346110264.07 620.01910284.28627.711410331.64641.3864
#Mann= 3 , 0 , 0
9638.448  0.0501       09638.448  0.0501       010331.64  0.0501       0
#XS Ineff= 2 , 0
       0                               0
Bank Sta=9638.448,10331.64
Exp/Cntr=0.3,0.1

Type RM Length L Ch R = 1 ,24232.12,247.893900,247.893900,247.893900
XS GIS Cut Line= 6
480478.230836121799934.981202158480404.131144159799810.696253535
480335.739912971799669.606138234480315.484411113799611.223305291
480300.631710457799550.934351263480294.238139029799509.626397696
#Sta/Elev= 30
9846.986658.17269853.295653.26839870.249634.6827 9892.35613.48039916.819595.7782
9928.461 588.1219931.405587.43829951.746585.9466 9970.46587.63969975.031587.3817
9986.673584.09689998.085582.526210020.55583.026610031.79583.944310054.27591.4825
10087.82598.813410098.91599.822410120.78597.021910131.71  602.9710142.64605.0667
10174.58608.113310206.34613.115710237.34 620.84910247.64624.547610257.94629.1505
10268.24631.092510278.43636.276110288.55639.270110298.67644.217310314.23 648.336
#Mann= 3 , 0 , 0
9846.986   0.071       09846.986   0.071       010314.23   0.071       0
#XS Ineff= 2 , 0
       0                               0
Bank Sta=9846.986,10314.23
Exp/Cntr=0.3,0.1

Type RM Length L Ch R = 1 ,23984.22,281.467200,281.467200,281.467200
XS GIS Cut Line= 6
480669.423602877799775.225798849 480586.90654451799618.013251195
480557.354332528799513.119721828480548.854759218799444.971212633
480551.843824382799323.724944924480585.936240507799172.770530288
#Sta/Elev= 30
9896.427 649.8819908.244644.73089925.207628.74819954.468606.22429966.023587.9541
9977.519580.78069988.987580.526810011.59580.953110066.56591.046610077.36592.2739
10087.92591.595910171.07  601.2710181.35604.222610191.46 609.23710201.54609.4268
10211.62607.648310251.93608.750110261.93612.897410271.93620.105710301.93635.4909
10362.06680.155510372.08684.2994 10382.2685.990310412.58683.713710432.83677.3619
 10453.3673.115810473.85673.534610505.18671.465510515.62674.486910528.39674.3691
#Mann= 3 , 0 , 0
9896.427  0.0864       09896.427  0.0864       010528.39  0.0864       0
#XS Ineff= 2 , 0
       0                               0
Bank Sta=9896.427,10528.39
Exp/Cntr=0.3,0.1

Type RM Length L Ch R = 1 ,23702.76,266.907600,266.907600,266.907600
XS GIS Cut Line= 6
480703.105438262  799814.4633369480817.965963699799725.223283129
480871.023963427 799611.29435355480951.881390793799473.818617993
481043.787405959  799342.2802151481112.247269191799256.188296046
#Sta/Elev= 30
9712.874647.09389727.937643.6105  9740.6 643.8319744.598642.49059778.591623.2843
9816.581 599.5679902.699599.05649935.793585.85889991.809577.4266 10011.4577.7501
10026.17580.320410037.76  583.6810049.36589.433210070.66608.873810084.15619.4233
10095.74631.721910118.94652.982210142.13672.341510154.09680.672210166.11680.1079
10178.13684.855210202.16697.991710226.45713.720810263.54723.983910275.91729.6521
10305.96747.533510325.97750.968910338.69748.936310402.53707.9404   10414705.0081
#Mann= 3 , 0 , 0
9712.874    0.12       09712.874    0.12       0   10414    0.12       0
#XS Ineff= 2 , 0
       0                               0
Bank Sta=9712.874,10414
Exp/Cntr=0.3,0.1

Type RM Length L Ch R = 1 ,23435.85,249.445800,249.445800,249.445800
XS GIS Cut Line= 6
480705.273548305799844.816877514480807.332882851799812.156630218
480974.929013908 799827.91319938481070.913087398799829.309763938
481236.266144127799815.079683349481371.142871499799786.374996617
#Sta/Elev= 30
9722.625638.05329732.837634.99539753.836  637.349764.336633.28739785.335619.9523
9806.334601.62729887.724598.2585 9897.82595.99379907.916589.45189918.012586.7937
9988.436575.443510028.46576.589510048.47586.409910058.47593.345410068.47605.3539
10098.47631.261410108.49642.218710168.56698.701510188.66715.270110198.73721.0802
10218.88738.385110228.96 748.58510239.03755.737310279.51762.297410289.68764.6916
10299.85769.804710330.36787.757110350.94 801.54310371.51816.872910398.41839.7383
#Mann= 3 , 0 , 0
9722.625    0.12       09722.625    0.12       010398.41    0.12       0
#XS Ineff= 2 , 0
       0                               0
Bank Sta=9722.625,10398.41
Exp/Cntr=0.3,0.1

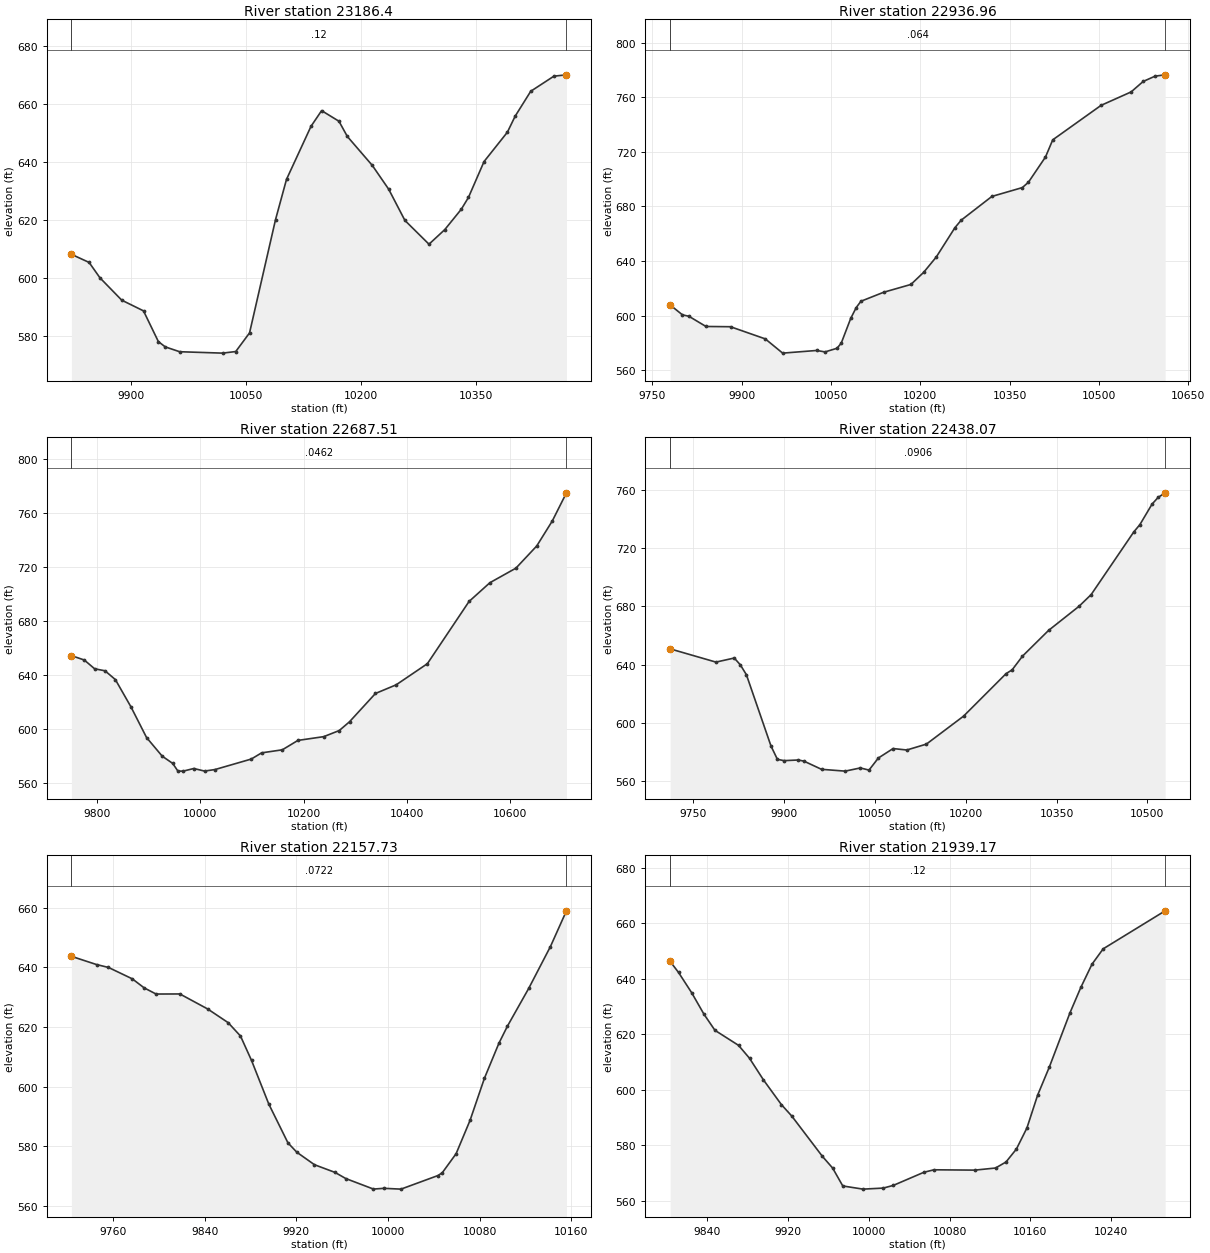
Type RM Length L Ch R = 1 , 23186.4,249.445700,249.445700,249.445700
XS GIS Cut Line= 6
480734.631858592799918.970194195480862.569050245800042.569905858
480972.513840942800118.789856321481048.067867752800153.393494111
481123.172615998800177.352539768481291.241628691 800205.05750916
#Sta/Elev= 30
9823.058608.20479846.088605.41119860.251600.09259888.578592.40359916.905588.7153
9936.235578.13849945.232576.29889963.993574.630810019.91574.148210037.01574.6984
10054.97581.117710088.82620.187210103.11634.0494   10135652.3282 10148.8657.7322
10171.38654.075710182.26648.838710214.82638.840310236.09630.661910257.25619.8902
10288.61611.688810309.16616.721410330.72623.764810339.96627.799810360.29640.1806
10390.67650.301110400.79655.820410421.05664.399610451.25669.612110467.56670.0735
#Mann= 3 , 0 , 0
9823.058    0.12       09823.058    0.12       010467.56    0.12       0
#XS Ineff= 2 , 0
       0                               0
Bank Sta=9823.058,10467.56
Exp/Cntr=0.3,0.1

Type RM Length L Ch R = 1 ,22936.96,249.445700,249.445700,249.445700
XS GIS Cut Line= 6
480527.509890308800067.558915537480598.386635654800125.361017887
480729.637216217800260.576996999480806.699967389 800312.20416087
 480980.64715906800368.275813096481251.829396749800411.577604547
#Sta/Elev= 30
9780.095607.8179 9800.82600.56239811.558599.54619840.263592.06429881.472591.8757
9939.855582.97249969.046572.542110026.32 574.49310040.12573.426810060.32576.1073
10067.37579.821210083.33597.9855 10092.6 605.94910100.47610.534410138.65617.1307
10184.39 622.83910205.81631.721410226.96642.940710258.34664.455510268.81669.9198
10320.35687.313410371.54693.792410381.75 697.73610410.34716.194710422.52728.7563
10503.65754.012110554.13763.853510574.27771.493610594.36775.407710611.27776.3743
#Mann= 3 , 0 , 0
9780.095   0.064       09780.095   0.064       010611.27   0.064       0
#XS Ineff= 2 , 0
       0                               0
Bank Sta=9780.095,10611.27
Exp/Cntr=0.3,0.1

Type RM Length L Ch R = 1 ,22687.51,249.445800,249.445800,249.445800
XS GIS Cut Line= 6
 480290.04261903800383.859186438480456.574882114800398.656024965
480586.390005378 800423.41988095480743.215181904800412.787950424
 480824.18403781800413.221067897 481242.28018208800461.615489375
#Sta/Elev= 30
9750.238654.1522  9775.2650.87649795.231644.37079815.309642.90539835.387636.3647
9865.554616.1659 9895.81593.39859926.125579.58969946.433  574.239956.587568.5066
9966.742568.49889987.258570.438410008.16568.539610028.41569.674510098.64577.4482
10118.71582.052210158.85584.306710188.96591.270310239.02594.067510269.02598.5759
10289.03605.120410339.19626.075510379.32632.486310439.82648.171710520.51 694.296
10560.86708.192810611.29718.991310651.64735.442710681.79753.9848 10709.2774.8551
#Mann= 3 , 0 , 0
9750.238  0.0462       09750.238  0.0462       0 10709.2  0.0462       0
#XS Ineff= 2 , 0
       0                               0
Bank Sta=9750.238,10709.2
Exp/Cntr=0.3,0.1

Type RM Length L Ch R = 1 ,22438.07,280.331500,280.331500,280.331500
XS GIS Cut Line= 6
  480441.7690214 800644.25859226480556.890341594800667.363942861
480619.584228382800656.342877236480745.304918036800537.182439932
480836.396499425800500.420683052481196.488393952 800516.76273519
#Sta/Elev= 30
9712.034650.78179787.688641.70629817.916644.50169827.956639.82989837.975633.0469
9878.581584.17419889.139575.04549900.131574.15139923.686574.59259933.046573.8011
9961.957568.2118   10001566.964910026.09569.149710040.38567.671510055.88575.9724
10080.16582.438610102.82581.446910135.18585.4844 10196.6604.686610266.72  633.81
10276.72636.393710293.78645.774510336.84663.423910387.05679.924810407.17687.9793
10477.58 730.95610487.64735.954510507.75750.025510517.81754.635510529.37757.7548
#Mann= 3 , 0 , 0
9712.034  0.0906       09712.034  0.0906       010529.37  0.0906       0
#XS Ineff= 2 , 0
       0                               0
Bank Sta=9712.034,10529.37
Exp/Cntr=0.3,0.1

Type RM Length L Ch R = 1 ,22157.73,218.559900,218.559900,218.559900
XS GIS Cut Line= 6
 480414.28559444800658.729760041480528.416789794800692.264326002
480563.933896296 800706.37893541480587.498910185800722.750344335
480678.532953616800852.169831486 480734.51030345800919.622198578
#Sta/Elev= 30
 9723.68643.69259745.587640.9368 9756.03639.96139776.802636.14299787.189633.1064
9797.575631.04159818.348631.06859842.669626.01979860.514621.43379871.274616.9465
9880.888608.77619895.998 594.102 9912.69581.10869920.452577.96159935.845573.7721
 9953.79571.19389963.234569.12419987.321565.60319996.396565.853910011.37565.5833
10043.71570.152210047.44571.099110059.47577.459410071.65588.650510084.23602.8128
10096.82614.502210104.27620.255410122.84632.916710141.83646.9792 10155.8658.9595
#Mann= 3 , 0 , 0
 9723.68  0.0722       0 9723.68  0.0722       0 10155.8  0.0722       0
#XS Ineff= 2 , 0
       0                               0
Bank Sta=9723.68,10155.8
Exp/Cntr=0.3,0.1

Type RM Length L Ch R = 1 ,21939.17,249.445800,249.445800,249.445800
XS GIS Cut Line= 6
480367.979281272800669.217776558480401.192030135800714.225114272
480414.593226705800746.297243454480446.761100853 800966.09817071
480474.130743405801050.741912233480515.693234377801128.595447532
#Sta/Elev= 30
9802.976646.21419811.308642.2315  9824.3634.95029836.522627.20219847.427621.3984
9870.835615.98049881.673611.34659895.528603.54019913.246594.68049923.581590.5314
9953.999576.00069964.113571.80499974.163565.36549994.244564.223910014.34564.5989
10024.39565.584610054.55570.2886 10064.6571.186210105.13 571.06610125.63571.8247
10135.99573.988110146.34 578.66510156.75586.2462 10167.4598.099110178.96608.1717
10199.35627.630210210.19636.836310221.26645.200310232.34650.731810293.81664.4196
#Mann= 3 , 0 , 0
9802.976    0.12       09802.976    0.12       010293.81    0.12       0
#XS Ineff= 2 , 0
       0                               0
Bank Sta=9802.976,10293.81
Exp/Cntr=0.3,0.1

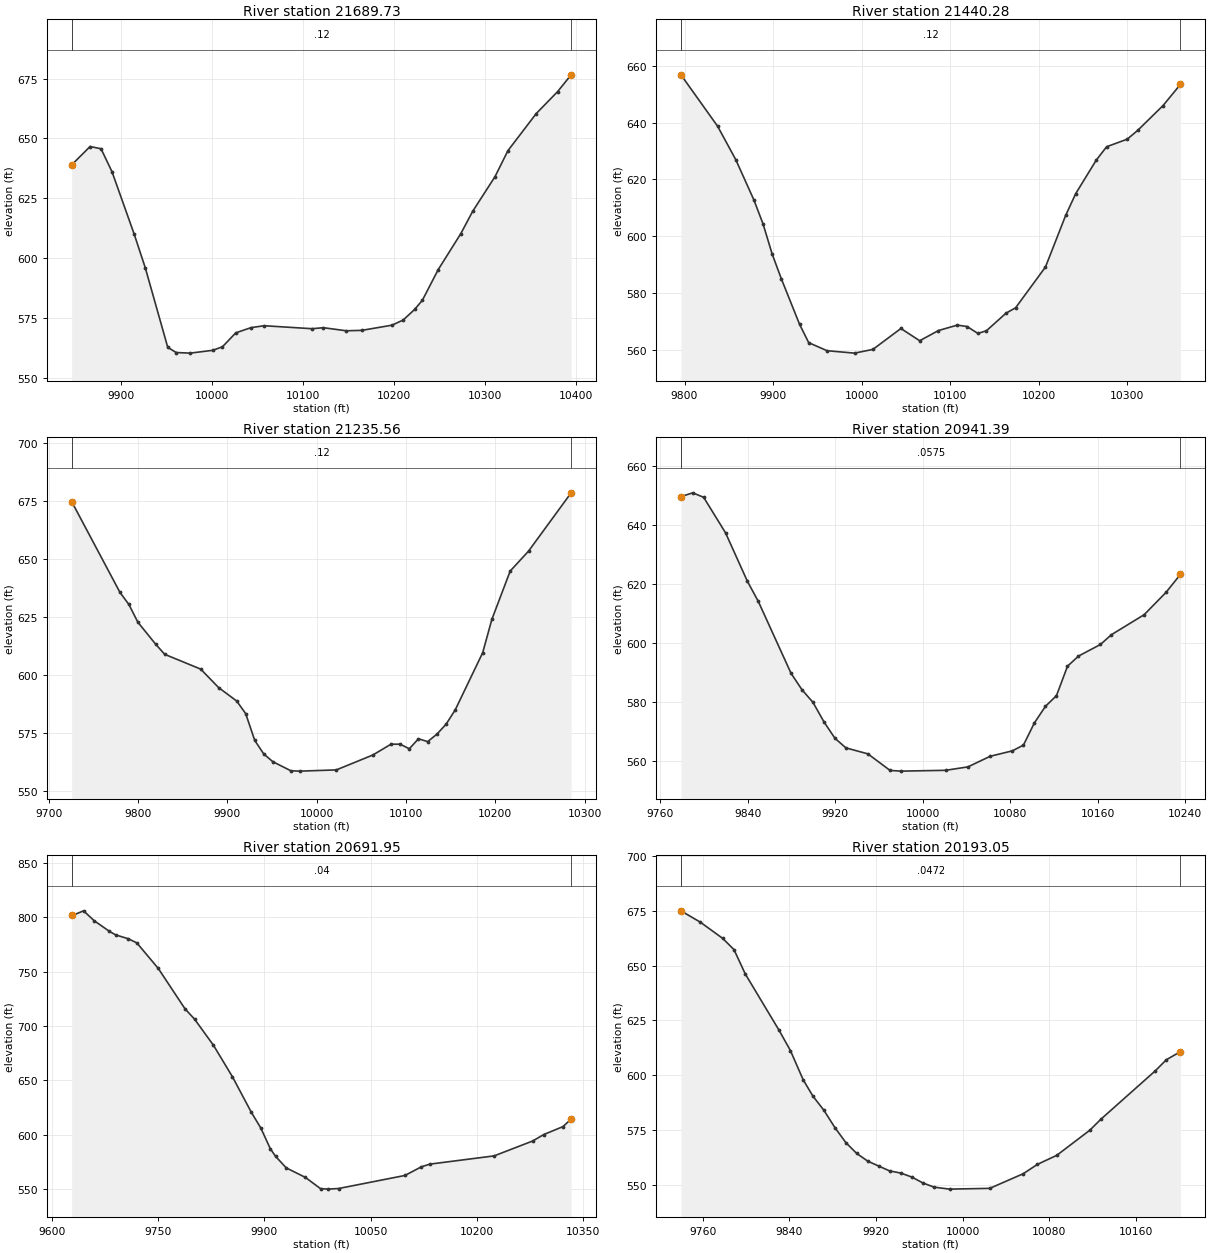
Type RM Length L Ch R = 1 ,21689.73,249.445700,249.445700,249.445700
XS GIS Cut Line= 6
480078.111321294800829.665657334480207.682213074800920.390336943
480249.980352406800956.874194439480365.473684499801105.738779848
480417.405600948801169.234664158480461.205111985801215.847601646
#Sta/Elev= 30
9846.197638.89279866.472646.57689878.478645.63529890.483 636.074 9914.78610.0802
9927.106595.8531 9951.76562.63099961.029560.46919976.413560.213310001.07561.3844
10011.83562.860710026.48568.686310043.11570.8585 10057.6571.667410110.24570.4214
10122.75570.841910147.78 569.55510164.86569.729410198.13571.902510210.35 574.056
10222.86578.4501 10231.4582.302110248.82595.1233 10273.7610.201310286.62619.4627
10311.25634.016710325.38644.848510356.54660.376510379.92669.513310394.81676.5435
#Mann= 3 , 0 , 0
9846.197    0.12       09846.197    0.12       010394.81    0.12       0
#XS Ineff= 2 , 0
       0                               0
Bank Sta=9846.197,10394.81
Exp/Cntr=0.3,0.1

Type RM Length L Ch R = 1 ,21440.28,204.719800,204.719800,204.719800
XS GIS Cut Line= 6
479894.499831179801092.075348356480011.669411559801118.639309548
480093.687174595801140.558325877480193.116990633801174.535972276
480266.955117067801208.016493304480416.487021683801295.120579885
#Sta/Elev= 30
 9795.93 656.8379837.352638.72369857.891626.94019878.431612.69929888.701   604.3
 9898.97593.7185 9909.24585.06379929.899 568.9829940.257562.48219960.975559.6448
9992.052558.793310012.82560.106310044.44567.474510065.66563.157810086.88566.7539
10108.16 568.66110119.14568.171910131.43565.7339 10141.1566.683810163.06572.8393
10174.04574.776710207.75589.124710230.57607.304110241.97615.009310265.16626.7934
10276.83631.494110300.17634.170710311.84637.226710340.62646.021210360.25653.4587
#Mann= 3 , 0 , 0
 9795.93    0.12       0 9795.93    0.12       010360.25    0.12       0
#XS Ineff= 2 , 0
       0                               0
Bank Sta=9795.93,10360.25
Exp/Cntr=0.3,0.1

Type RM Length L Ch R = 1 ,21235.56,294.171700,294.171700,294.171700
XS GIS Cut Line= 6
479791.031573393801310.984354375479901.772921634801319.470278103
479983.804382709801329.756176947  480057.1083832801341.745375186
480310.317865526801398.684839212480341.797868801801404.284698037
#Sta/Elev= 30
9725.403 674.7349779.501635.64379789.538630.42139799.575622.80139819.649613.2765
9829.686608.96749869.971602.61239890.128594.63019910.285588.8858 9920.37583.4643
9930.502571.94569940.635566.07859950.768562.77169971.034558.84799981.167558.7055
10021.92559.228310062.79565.638710083.23570.315610093.45570.291410103.68568.3256
10113.96572.631310124.23571.396910134.51574.589310144.78578.854210155.05585.0126
10185.88 609.66710196.15624.0108 10216.7644.815210237.25653.390810284.96678.4728
#Mann= 3 , 0 , 0
9725.403    0.12       09725.403    0.12       010284.96    0.12       0
#XS Ineff= 2 , 0
       0                               0
Bank Sta=9725.403,10284.96
Exp/Cntr=0.3,0.1

Type RM Length L Ch R = 1 ,20941.39,249.445700,249.445700,249.445700
XS GIS Cut Line= 6
 479784.23959996 801616.72982341 479844.91445986801615.285013374
479951.911380507801621.987141232480082.864149315801646.473084879
480157.206154194801655.557299642480237.882330108801651.405657572
#Sta/Elev= 30
9778.785649.50479789.549650.78649799.552649.27359819.557637.26669839.563 620.854
9849.568614.01869879.584589.63679889.589584.08539899.616579.8233 9909.66573.2209
9919.704567.67319929.748564.41899949.869562.39349970.168556.77699980.317556.5492
10021.01556.823910041.39557.986410061.76561.580710082.12563.422910092.19565.3716
10102.26572.911610112.34578.494310122.41582.109510132.49592.061310142.56595.5071
10162.66599.434310172.66602.737610202.71609.537610222.78617.128910235.85623.1698
#Mann= 3 , 0 , 0
9778.785  0.0575       09778.785  0.0575       010235.85  0.0575       0
#XS Ineff= 2 , 0
       0                               0
Bank Sta=9778.785,10235.85
Exp/Cntr=0.3,0.1

Type RM Length L Ch R = 1 ,20691.95,498.891500,498.891500,498.891500
XS GIS Cut Line= 6
 479725.28780821802106.155653939479959.462418646801898.200625464
480076.273160368801852.915820822480130.740317315 801823.58534506
 480191.83829695801775.807043374480282.691746086801686.882955939
#Sta/Elev= 30
9627.784802.16139629.525801.66049644.585805.75279659.645796.64159680.895787.0087
9689.765783.67589707.643 780.1399719.885776.25839750.006752.90819787.886715.6959
 9801.26706.31199828.008682.25339854.755653.37649881.503 620.6559894.877606.2274
9908.251587.25219915.667580.26749930.727569.65679957.655560.96219979.136550.5815
9989.877550.143410004.75550.7194 10098.3562.7002 10121.5570.643310133.41573.0939
 10224.2580.667910278.42594.292410294.17600.246610321.31607.542510332.92614.4398
#Mann= 3 , 0 , 0
9627.784    0.04       09627.784    0.04       010332.92    0.04       0
#XS Ineff= 2 , 0
       0                               0
Bank Sta=9627.784,10332.92
Exp/Cntr=0.3,0.1

Type RM Length L Ch R = 1 ,20193.05,249.445700,249.445700,249.445700
XS GIS Cut Line= 6
480442.932232916802182.039505497480477.973691434 802063.58435899
480469.709224075802006.836584821480430.406203717801844.209504515
480420.057449371801792.202675298480414.793255389801731.949609891
#Sta/Elev= 30
9739.661674.92379757.431669.80919778.287662.37139788.716657.24329799.144646.1784
9830.429620.49049840.858611.30669852.708597.94759861.714 590.5189871.866584.0885
9881.971576.24549892.077569.41919902.182564.43939912.288560.98049922.416558.7149
9932.647556.49679942.878555.5328 9953.11553.70539963.341551.02689973.572549.1193
9987.955548.208210025.15548.5591 10056.1555.218910069.22559.485810087.05563.5796
10117.65575.026210127.85580.022210178.34602.134310188.39607.118210201.44610.7927
#Mann= 3 , 0 , 0
9739.661  0.0472       09739.661  0.0472       010201.44  0.0472       0
#XS Ineff= 2 , 0
       0                               0
Bank Sta=9739.661,10201.44
Exp/Cntr=0.3,0.1

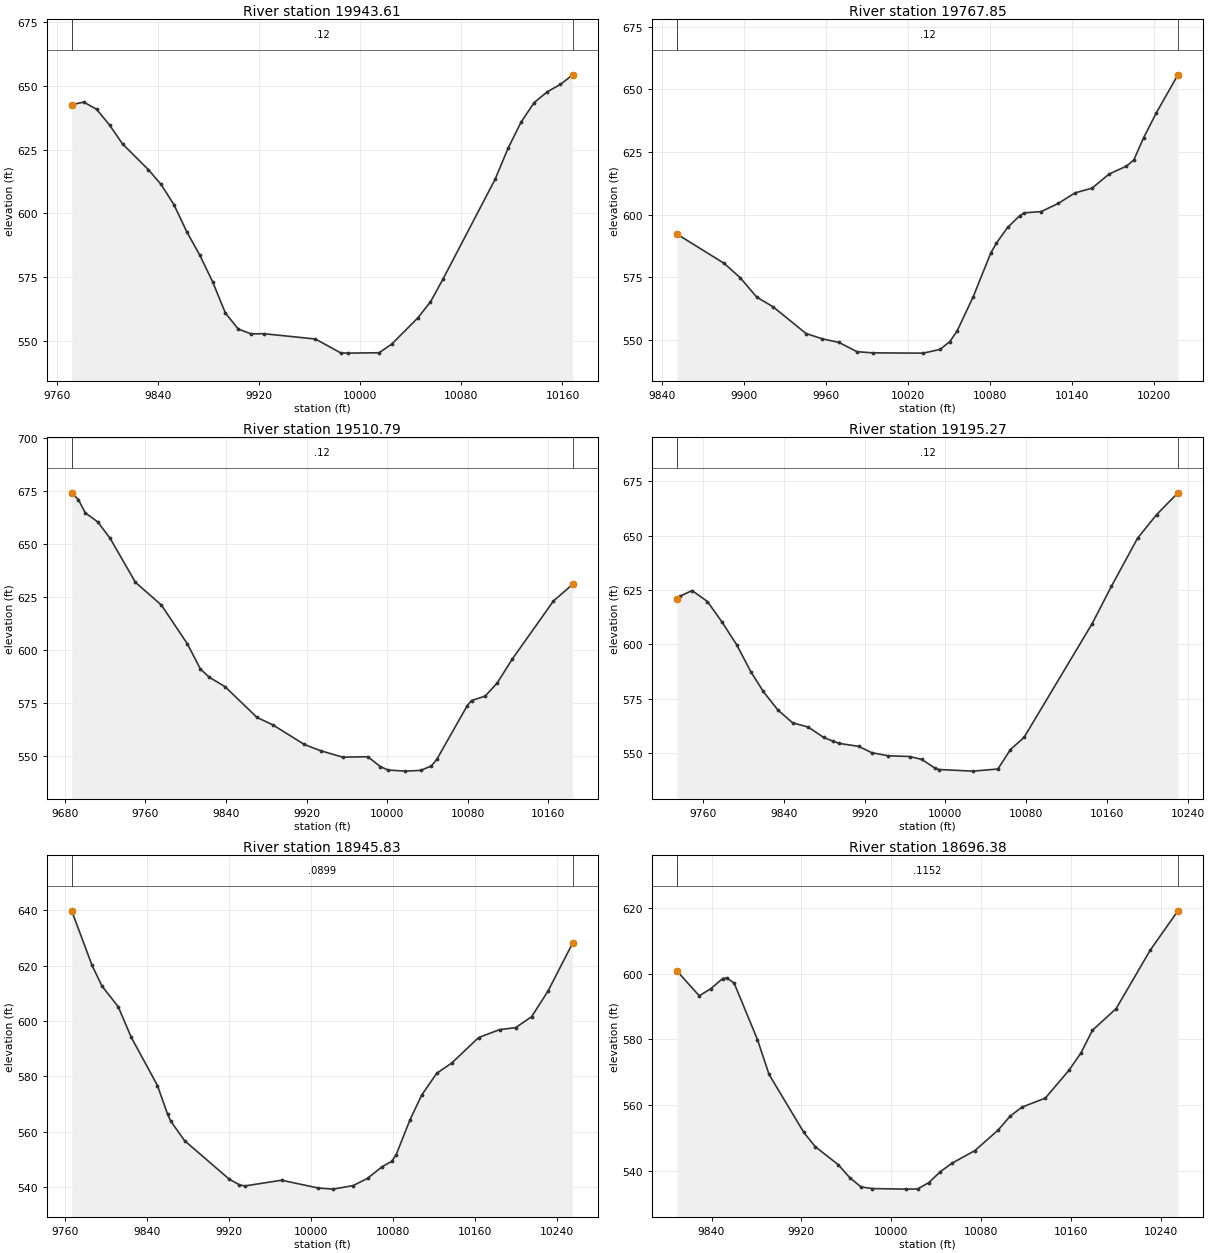
Type RM Length L Ch R = 1 ,19943.61,175.763100,175.763100,175.763100
XS GIS Cut Line= 6
480655.928268031802124.287345572480690.297193122801945.094472969
480699.708701372801871.448975201480708.984346548801821.343955583
480723.166852034801762.352816298480731.079841293801735.751030888
#Sta/Elev= 30
9771.962642.56479781.456643.59069791.678640.7538  9801.9634.58939812.123627.2236
9832.478617.18259842.648611.31689852.819603.3788 9862.99592.74499873.161583.7033
9883.332573.25249893.502560.94329903.673554.69249913.844552.80919924.015552.8644
9964.614550.79449984.789545.32589990.211545.264110015.03 545.416 10025.1 548.846
10045.41558.960610055.58565.303310065.75574.483110106.73613.352310117.01625.5332
 10127.3635.769110137.58643.368910147.98647.620910158.41650.523410168.06654.2647
#Mann= 3 , 0 , 0
9771.962    0.12       09771.962    0.12       010168.06    0.12       0
#XS Ineff= 2 , 0
       0                               0
Bank Sta=9771.962,10168.06
Exp/Cntr=0.3,0.1

Type RM Length L Ch R = 1 ,19767.85,257.053500,257.053500,257.053500
XS GIS Cut Line= 6
480773.073370497 802094.79553734480796.613229387802055.434668401
480835.268242977801997.958911852480842.046219991 801988.42009139
 480941.45429218801851.392325725480984.646139426 801795.10384272
#Sta/Elev= 30
 9850.77592.23519885.487580.49839897.156 574.7999909.207567.07579921.259563.1808
9945.361 552.5349957.412 550.3939969.526548.9726 9982.63 545.2879994.179544.8094
10031.24544.7053 10043.6  546.1910050.75549.342610055.95553.450410067.78567.1345
10080.66584.609710084.81588.590910093.01594.862710101.84599.533210105.37 600.727
10117.72601.224210130.08604.452310142.43608.673410154.95610.588210167.55616.2533
10180.15619.358910185.57621.860910192.76630.759810201.99 640.59910217.84655.8152
#Mann= 3 , 0 , 0
 9850.77    0.12       0 9850.77    0.12       010217.84    0.12       0
#XS Ineff= 2 , 0
       0                               0
Bank Sta=9850.77,10217.84
Exp/Cntr=0.3,0.1

Type RM Length L Ch R = 1 ,19510.79,315.520700,315.520700,315.520700
XS GIS Cut Line= 6
480871.087885955802365.950625833480902.955624518802321.916091138
481025.416598101802172.021081754 481074.00615401802106.620265074
481100.110834796802074.606607445481186.054701466801981.179744342
#Sta/Elev= 30
9686.714674.17139693.387670.92079700.231664.70769712.575660.49119724.919652.7001
9750.001632.02489775.827 621.3049801.653602.99629814.566591.1763 9823.33587.3094
9839.136582.82749870.748568.37559886.553564.8581 9917.87 555.6169933.971 552.687
9955.885549.65359980.861549.85649993.275545.226810000.92543.5853 10018.2543.0713
 10033.5543.4196   10044545.535810049.33548.566610079.58573.872610083.88576.3387
10097.38578.398810109.35584.547910124.24595.773510165.17623.164510184.37631.0915
#Mann= 3 , 0 , 0
9686.714    0.12       09686.714    0.12       010184.37    0.12       0
#XS Ineff= 2 , 0
       0                               0
Bank Sta=9686.714,10184.37
Exp/Cntr=0.3,0.1

Type RM Length L Ch R = 1 ,19195.27,249.445700,249.445700,249.445700
XS GIS Cut Line= 6
481074.236243052802525.852074933481118.673482975 802479.35461616
 481189.32513599802415.439223562481229.134477366802383.826634529
481397.916708956802259.174787308481455.182239515802210.934139114
#Sta/Elev= 30
 9734.61620.85289737.139622.05419749.521624.79959764.745619.74179779.186610.2756
9793.626599.86529807.635587.44749819.831 578.4139834.391569.80349849.048563.8846
9864.332561.97379879.615557.19439888.507555.52899894.933 554.4319914.242553.0852
9927.012550.19539943.174548.74149964.802548.3913  9976.7547.05469989.687543.0244
9993.505542.4188 10027.2541.675410051.83542.646410064.26551.605210077.72557.2135
10145.07609.603810164.04626.721110189.89648.866810208.66659.710710229.78669.7651
#Mann= 3 , 0 , 0
 9734.61    0.12       0 9734.61    0.12       010229.78    0.12       0
#XS Ineff= 2 , 0
       0                               0
Bank Sta=9734.61,10229.78
Exp/Cntr=0.3,0.1

Type RM Length L Ch R = 1 ,18945.83,249.445700,249.445700,249.445700
XS GIS Cut Line= 6
481276.561591535802720.543622746481332.989406892802649.624266305
481388.772380009802586.877719787481527.337021959802442.465618546
481581.980679335802376.834507329481599.294314228802353.288749519
#Sta/Elev= 30
9766.162639.85979786.025620.16139795.776612.63749811.584 605.2249824.363594.1224
9849.921576.74079859.817566.37059862.978563.80479876.359556.8346 9920.02542.9003
9929.881540.88149935.071540.43789971.179542.518710007.17539.690210021.42539.2985
10041.11540.577110055.14543.184710069.18547.352610078.61549.317410082.92551.5635
10096.55564.295510108.04573.285210122.75581.170310137.45584.884210163.63594.0637
10184.14596.932310199.77 597.64910215.39601.5979 10231.4610.837210255.53628.2354
#Mann= 3 , 0 , 0
9766.162  0.0899       09766.162  0.0899       010255.53  0.0899       0
#XS Ineff= 2 , 0
       0                               0
Bank Sta=9766.162,10255.53
Exp/Cntr=0.3,0.1

Type RM Length L Ch R = 1 ,18696.38,249.445800,249.445800,249.445800
XS GIS Cut Line= 6
481593.149403846802864.059404712481619.943549886802766.151274318
481631.072566801802711.915846809481638.542796276802643.945261747
481650.915607114802592.039253752481703.296364397802433.238550283
#Sta/Elev= 30
9809.211600.81449829.058593.25469839.415595.43549849.773598.47629853.358598.7352
 9860.13597.10839880.846579.96059891.203 569.3369922.109551.72979932.318547.3774
9952.735541.92279962.943537.98279973.047 535.1399983.104534.637810013.28534.4702
10023.35534.518810033.41536.451910043.67539.789810053.95542.344910074.51546.2098
10095.21552.480110105.68556.633910116.15559.3773 10137.1562.155410158.05 570.595
10168.52575.7316   10179582.776910200.12589.366510230.41607.114410255.08619.0946
#Mann= 3 , 0 , 0
9809.211  0.1152       09809.211  0.1152       010255.08  0.1152       0
#XS Ineff= 2 , 0
       0                               0
Bank Sta=9809.211,10255.08
Exp/Cntr=0.3,0.1