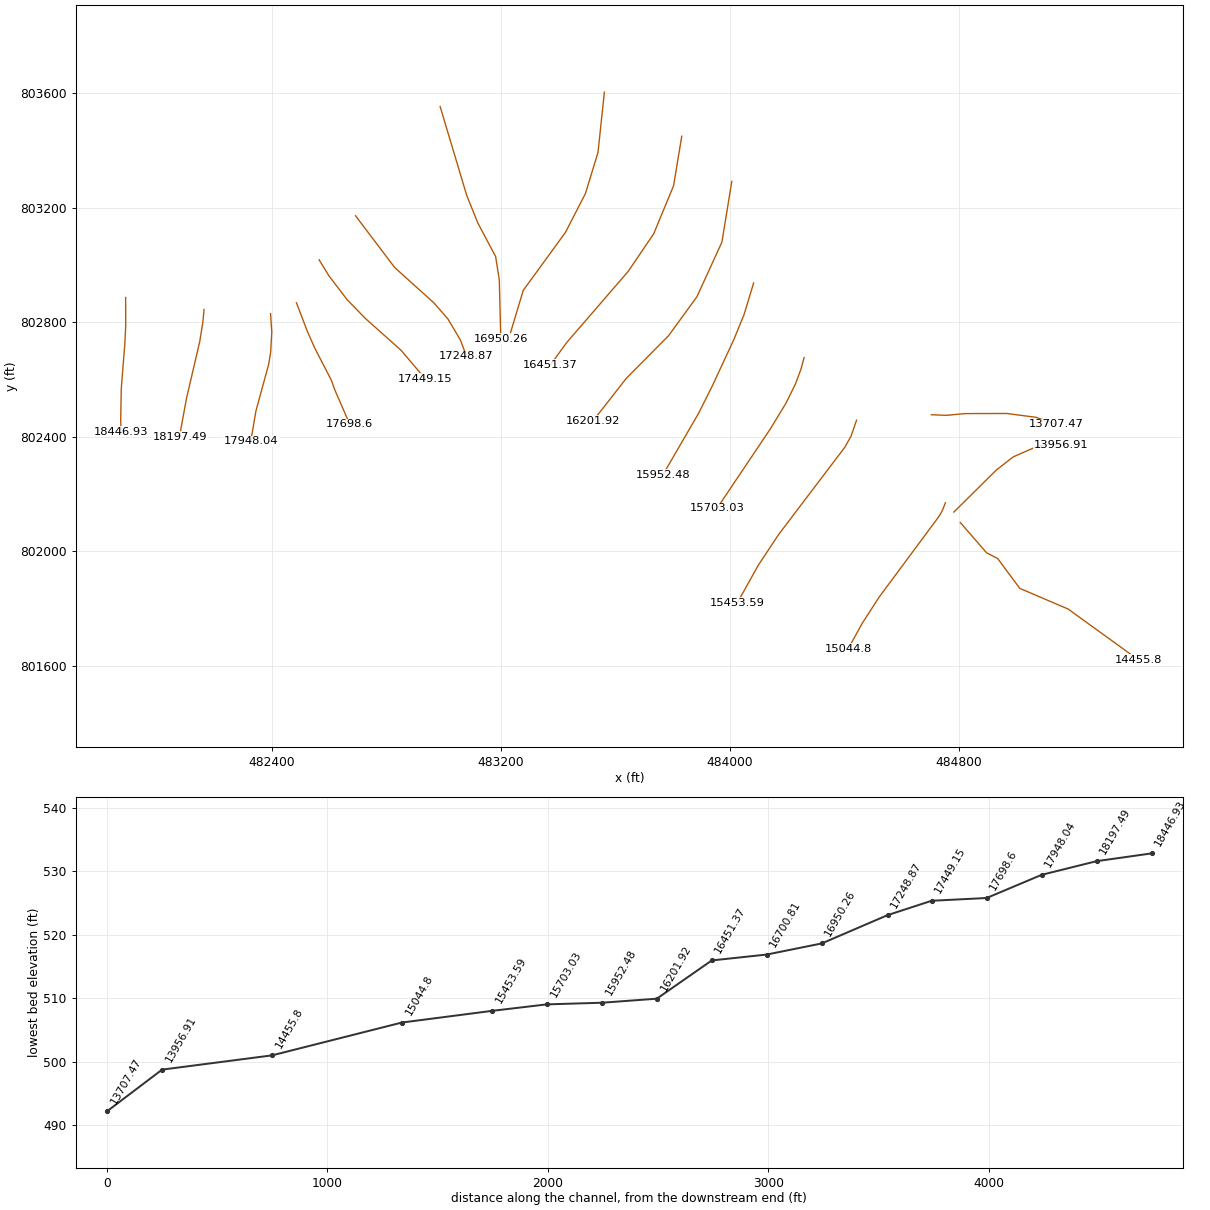
HEC-RAS study 5528_ras.prj: 5528

--- 5528_ras.g01 (geometry) --- (continued)

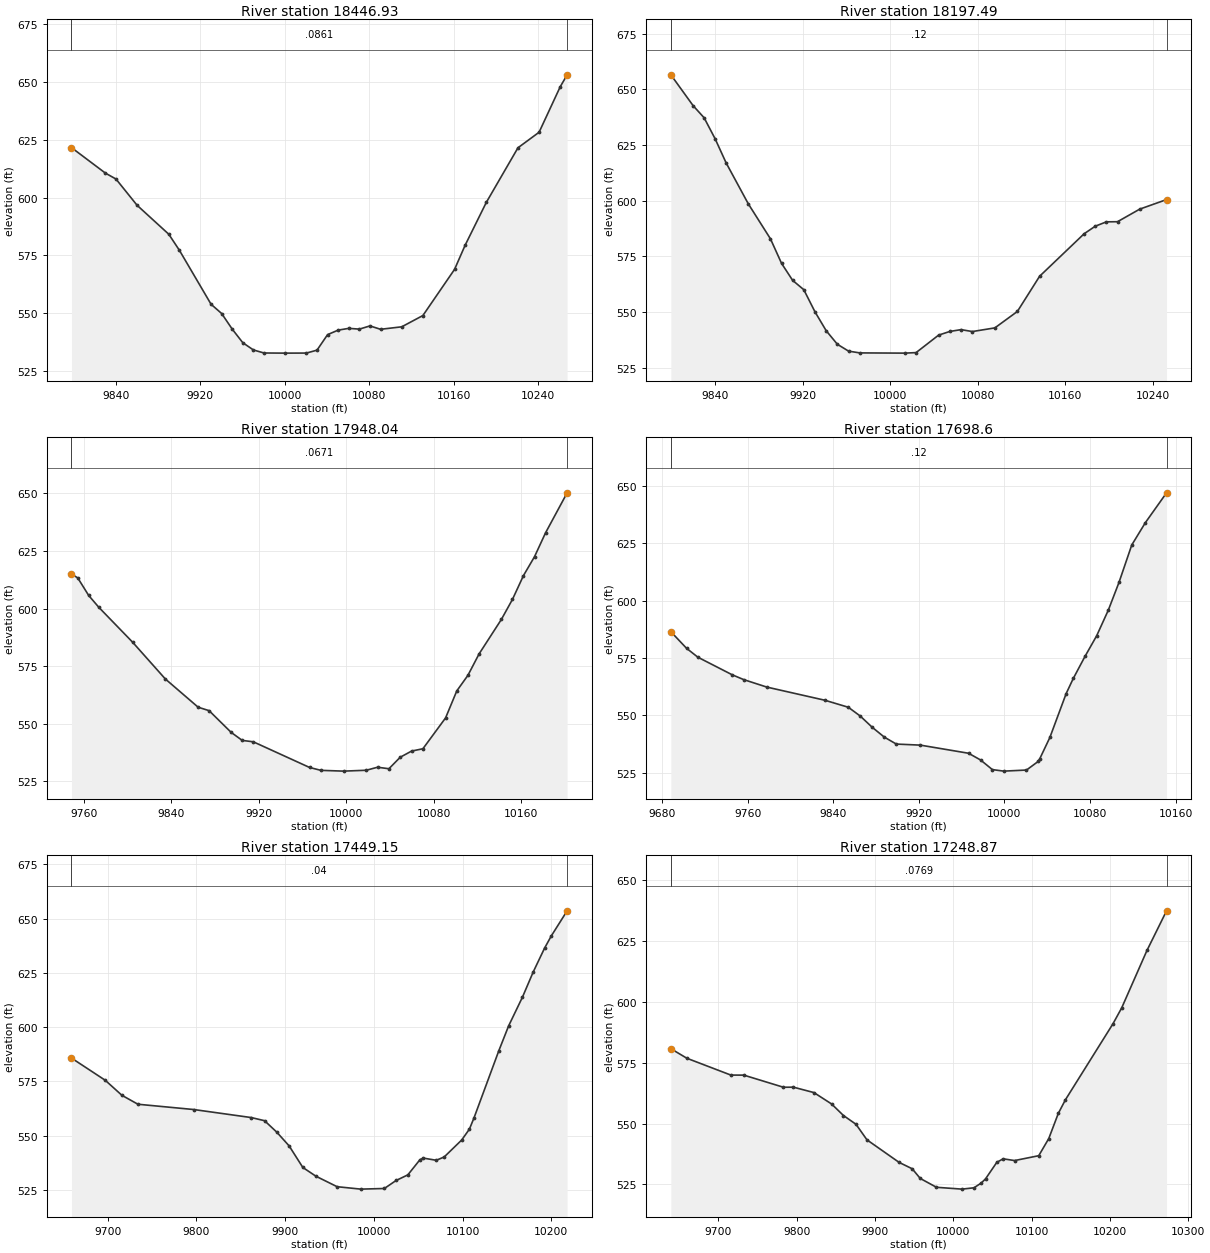
Type RM Length L Ch R = 1 ,18446.93,249.445700,249.445700,249.445700
XS GIS Cut Line= 6
481889.636118224802887.150865369481889.933042571802787.959063762
 481886.85756348802726.695321952481874.404606591  802569.0965877
 481872.33923156 802459.44002573481873.795812887  802418.4766933
#Sta/Elev= 30
 9797.98621.58089830.143610.54619840.143608.00029860.143596.64919890.143 584.151
9900.147577.24629930.185553.89299940.198549.8974 9950.21 543.1499960.227537.2819
9970.262534.15589980.297532.848710000.37532.789810020.43532.818710030.46534.0723
10040.49540.780310050.52542.730410060.55543.486110070.58543.163510080.61544.5469
10090.64543.0831 10110.7544.156810130.72549.031810160.72568.980810170.72579.4048
10190.73597.872910220.73621.493810240.74 628.20910260.75647.862910267.28653.0133
#Mann= 3 , 0 , 0
 9797.98  0.0861       0 9797.98  0.0861       010267.28  0.0861       0
#XS Ineff= 2 , 0
       0                               0
Bank Sta=9797.98,10267.28
Exp/Cntr=0.3,0.1

Type RM Length L Ch R = 1 ,18197.49,249.445700,249.445700,249.445700
XS GIS Cut Line= 6
482163.456835094 802845.23953119482159.175275324802799.604108471
482148.573207143802733.858629551482102.154166042802534.719789431
482082.324488139802426.852078463482079.002256513 802400.70990165
#Sta/Elev= 30
9799.701656.52549820.029642.68029830.073 637.2479840.117627.8274  9850.2616.9798
9870.459598.59569890.717582.87589900.846571.86859910.975 564.2389921.189560.0368
9931.414550.08669941.639541.62759951.863535.53759962.088532.46379972.353531.6695
 10013.5531.569410023.78531.803510044.35539.650510054.63541.306210064.91542.1189
 10075.2541.260210095.77542.902510116.33 550.27410136.67566.090510177.34585.1683
10187.51588.556910197.68590.515610207.85590.575510228.16596.226110252.65600.5081
#Mann= 3 , 0 , 0
9799.701    0.12       09799.701    0.12       010252.65    0.12       0
#XS Ineff= 2 , 0
       0                               0
Bank Sta=9799.701,10252.65
Exp/Cntr=0.3,0.1

Type RM Length L Ch R = 1 ,17948.04,249.445800,249.445800,249.445800
XS GIS Cut Line= 6
482395.738826668 802830.70217917482399.993662489 802766.59927936
482396.148374895802696.159863303482388.997071697 802652.92862632
482344.751013903802491.193004335482326.717820625802385.462244659
#Sta/Elev= 30
9748.551614.96929754.288613.31249764.349 605.6669773.733600.46179804.428585.4391
9834.438569.44099864.508557.16169874.544555.66429894.727546.23659904.863542.7528
9914.999542.14459966.523 530.9969976.882529.7555  9997.6529.416110018.36 529.794
10028.73531.1094 10039.1530.450510049.48 535.45510059.85 538.12110070.22539.1316
10090.97552.518410101.23564.241910111.42571.006810121.62580.2936   10142595.2505
10152.18603.969310162.28614.324810172.38622.514710182.48632.882710202.21650.2315
#Mann= 3 , 0 , 0
9748.551  0.0671       09748.551  0.0671       010202.21  0.0671       0
#XS Ineff= 2 , 0
       0                               0
Bank Sta=9748.551,10202.21
Exp/Cntr=0.3,0.1

Type RM Length L Ch R = 1 , 17698.6,249.445700,249.445700,249.445700
XS GIS Cut Line= 6
482486.092625402802868.803178637482524.014785528 802769.79715769
482550.170650611802710.372288208482607.807978092802598.692998167
482620.361134485802564.089852895482672.112825932802444.902184425
#Sta/Elev= 30
 9688.17586.47999702.841579.25319713.469575.35689745.562567.70969756.323565.6114
9777.844 562.3729832.222556.62989854.074553.58039865.175549.77029876.429544.8551
9887.682540.59289898.935537.55639921.442537.09519966.455533.55669977.708530.6339
9988.739526.43599999.384525.774210020.65526.245310031.56529.988210033.07531.1782
 10042.5540.429810057.75 559.55910064.37566.106510075.31575.702510086.25584.7064
10097.19595.918110107.11607.927810119.06624.235310131.79  633.9710151.58 646.948
#Mann= 3 , 0 , 0
 9688.17    0.12       0 9688.17    0.12       010151.58    0.12       0
#XS Ineff= 2 , 0
       0                               0
Bank Sta=9688.17,10151.58
Exp/Cntr=0.3,0.1

Type RM Length L Ch R = 1 ,17449.15,200.279200,200.279200,200.279200
XS GIS Cut Line= 6
482565.238102756803018.759256102482600.787131218802961.214692098
482663.184407668 802879.57212529482726.022267459802814.758361321
 482851.28289533 802703.07788138 482935.27102924 802604.17457342
#Sta/Elev= 30
9659.267585.74659697.363575.50179716.086568.59149734.185564.45929797.003562.0245
9862.015558.31299876.874556.87529890.567551.63269904.583545.25569920.033535.3181
9934.795531.28539958.652526.45799985.306525.340510011.87525.633110025.11  529.32
10038.36531.913710051.93538.869310055.72539.645110070.39538.637310079.28540.1513
10099.04547.976410107.72552.988810112.87558.126610140.89589.131510151.93600.5783
10167.53613.832410179.65625.431810192.35 636.33610200.02 642.03310217.84  653.59
#Mann= 3 , 0 , 0
9659.267    0.04       09659.267    0.04       010217.84    0.04       0
#XS Ineff= 2 , 0
       0                               0
Bank Sta=9659.267,10217.84
Exp/Cntr=0.3,0.1

Type RM Length L Ch R = 1 ,17248.87,298.612300,298.612300,298.612300
XS GIS Cut Line= 6
482692.712427731803172.429046132 482829.01595822802992.072600069
482966.624838166802868.048367974483015.556695236802811.783008614
483058.879052183802738.338154901483080.280921578802681.396156627
#Sta/Elev= 30
9639.527580.81049659.991576.87959716.072569.9738 9732.66 569.9469783.275564.9624
9795.928     565 9822.15562.77649844.695558.0925 9859.86553.3435 9875.86549.7404
9889.873 543.342 9930.96534.06049947.563531.45979957.934 527.4639978.635523.8307
10011.26523.078510026.48523.629110035.62525.561410041.21527.285310055.63534.0984
10063.71535.540310078.35534.826710109.16536.823610121.96543.867610134.19554.2497
 10143.3559.853910203.96591.076810215.05597.586610247.31621.198910272.32637.4994
#Mann= 3 , 0 , 0
9639.527  0.0769       09639.527  0.0769       010272.32  0.0769       0
#XS Ineff= 2 , 0
       0                               0
Bank Sta=9639.527,10272.32
Exp/Cntr=0.3,0.1

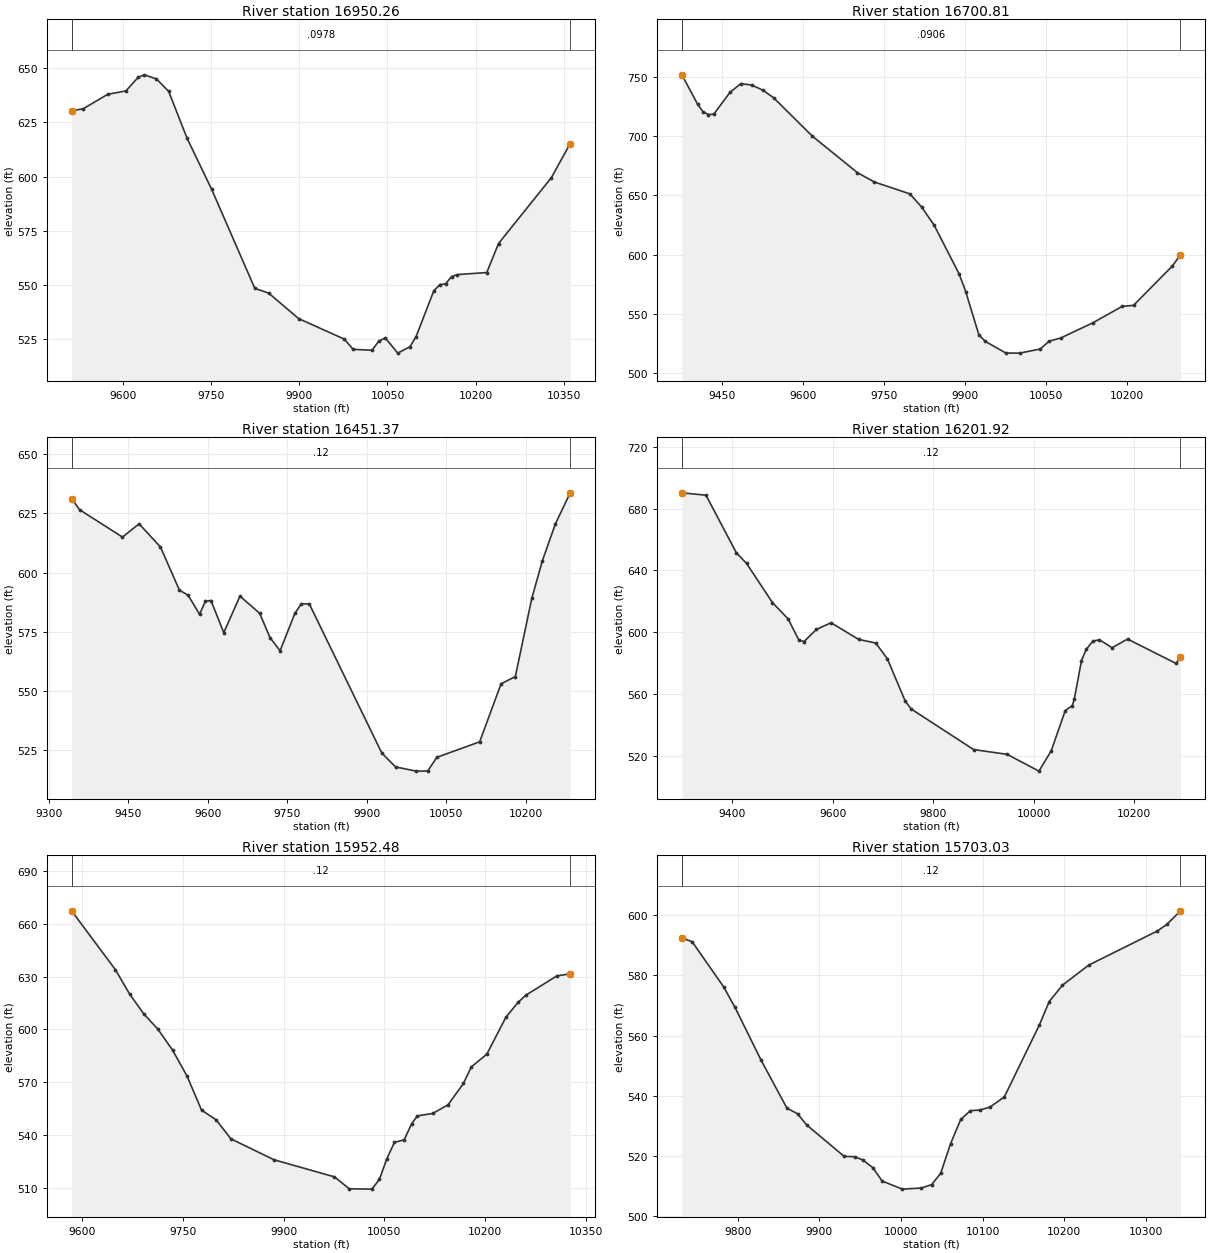
Type RM Length L Ch R = 1 ,16950.26,249.445700,249.445700,249.445700
XS GIS Cut Line= 6
482988.073627461  803553.9258214483080.682310266803244.265284737
483119.525435054 803147.64982208483181.834597448803030.138166232
483194.635870316802949.200334911483199.879269403 802742.95511895
#Sta/Elev= 30
9512.004630.34649531.693631.19539573.396637.87199604.515639.44359625.322645.7013
9635.725646.85549656.531644.95589677.338639.24159708.639617.64689750.583 594.063
9823.987548.48859847.651546.27759898.623 534.5379976.594525.06079991.408 520.371
10023.61519.951210034.92524.078610046.19525.630710067.57518.627910088.35521.6088
 10098.6526.205410128.83547.302710138.91550.167210148.98550.583810159.03553.8859
10169.04554.8133 10219.1555.7669 10239.1569.134310329.11599.489310361.16615.1974
#Mann= 3 , 0 , 0
9512.004  0.0978       09512.004  0.0978       010361.16  0.0978       0
#XS Ineff= 2 , 0
       0                               0
Bank Sta=9512.004,10361.16
Exp/Cntr=0.3,0.1

Type RM Length L Ch R = 1 ,16700.81,249.445800,249.445800,249.445800
XS GIS Cut Line= 6
483561.651219483 803604.23964526483539.331064444803393.543905692
483495.348924047803249.878204297483425.574378784803114.226579479
483278.283366085802912.013526781483232.587312093802760.109686781
#Sta/Elev= 30
9375.012751.44599404.259726.63619414.273720.31579424.287717.91719434.301718.3789
9464.386 736.7269484.492744.01559504.618742.81979524.912738.62049545.206732.1343
9616.746 699.9029700.453669.07019732.225661.11039797.976651.11759820.196639.8775
9843.289624.53519889.474583.61939901.658568.78029926.132532.22739938.369526.6838
9976.025516.978210001.66516.881910040.02520.384210056.44526.935410078.38529.7238
10137.43542.403310192.04556.292510213.04557.150810285.07590.309810300.17599.8195
#Mann= 3 , 0 , 0
9375.012  0.0906       09375.012  0.0906       010300.17  0.0906       0
#XS Ineff= 2 , 0
       0                               0
Bank Sta=9375.012,10300.17
Exp/Cntr=0.3,0.1

Type RM Length L Ch R = 1 ,16451.37,249.445700,249.445700,249.445700
XS GIS Cut Line= 6
483831.865345951 803450.35640546483803.381167995 803277.52021612
483733.837645048 803109.47795683483644.494701345802977.859336963
483430.339566658802730.238275741483373.341041996802651.631184917
#Sta/Elev= 30
9342.776 631.2529358.147626.53039438.876614.99949470.221620.6074 9510.59 610.822
9546.332592.55189562.882590.36869584.424582.34819595.195587.76719605.966588.1613
9630.137574.54539660.712590.00359697.948582.74969717.513572.41899736.513566.8949
9764.457582.72259776.279586.68229791.559586.77759928.569523.63179954.611517.7271
9993.672515.955910015.26516.003910032.58521.791910113.42528.363510153.83552.9119
10180.78555.961510211.91589.125110231.89 605.02910256.35620.557410284.37633.7264
#Mann= 3 , 0 , 0
9342.776    0.12       09342.776    0.12       010284.37    0.12       0
#XS Ineff= 2 , 0
       0                               0
Bank Sta=9342.776,10284.37
Exp/Cntr=0.3,0.1

Type RM Length L Ch R = 1 ,16201.92,249.445700,249.445700,249.445700
XS GIS Cut Line= 6
484006.691321106 803292.83993277483972.133957157803080.384464306
483884.783165239802889.603187496483786.331203821802754.257872644
483638.062939167802604.517183631 483523.07723374802457.481715976
#Sta/Elev= 30
9300.206690.25779348.129688.71919408.603651.3504 9428.95644.47459480.192619.1852
9511.308608.61119532.347595.16259542.911593.81049567.601601.71199596.775606.0724
9651.601595.30279685.667592.93239708.698582.79219744.025555.51699756.075550.2366
9880.229 523.9189946.919520.8182 10010.2509.938210034.58523.065810062.54549.1967
10076.41552.309210080.38556.373610094.81581.587510104.15588.776410117.36594.1696
10130.53595.047610155.61589.878310186.44595.508710282.74579.731810291.67583.6273
#Mann= 3 , 0 , 0
9300.206    0.12       09300.206    0.12       010291.67    0.12       0
#XS Ineff= 2 , 0
       0                               0
Bank Sta=9300.206,10291.67
Exp/Cntr=0.3,0.1

Type RM Length L Ch R = 1 ,15952.48,249.445800,249.445800,249.445800
XS GIS Cut Line= 6
484082.912374354802937.851642213484049.499518899802827.552316695
484013.504725177 802739.57838613 483938.91941828802578.889895973
483890.454649213802482.129022656483766.150787396802268.081546031
#Sta/Elev= 30
 9583.79667.33589649.016 633.9419670.133620.19829691.249 608.8949712.675  600.03
9734.284588.23439755.893573.49699777.503554.18139799.213548.65799821.262537.8587
9885.622525.96259975.638516.27029997.839 509.47310031.46509.302710042.67514.8493
10053.89526.683510065.11535.894910079.54537.288310090.73546.395710099.16 550.868
10122.07552.270610144.97557.169310167.93569.319510179.56578.646710202.81585.9528
10231.26606.9475 10249.3615.297910260.92619.436610307.42630.419910327.09631.5412
#Mann= 3 , 0 , 0
 9583.79    0.12       0 9583.79    0.12       010327.09    0.12       0
#XS Ineff= 2 , 0
       0                               0
Bank Sta=9583.79,10327.09
Exp/Cntr=0.3,0.1

Type RM Length L Ch R = 1 ,15703.03,249.445700,249.445700,249.445700
XS GIS Cut Line= 6
484259.185258237802677.137847939484248.232390762802636.595894978
484228.556636953802584.150080755484195.974512804802518.041513028
 484141.06827392802427.894276102483955.298878455802150.989870581
#Sta/Elev= 30
9731.749592.45089744.322591.19339782.946576.1848 9796.81569.38369828.851551.8097
9860.425535.93249873.406534.06799884.555530.36489930.388519.94419943.993519.7857
9953.761518.65429965.447516.21839977.134511.715210001.82509.0447 10024.6509.3995
10037.63510.521810048.77514.311210060.86524.129510073.25 532.16210085.03535.0851
10097.11 535.321 10109.2536.310110126.68539.641310169.62563.537410181.71571.3304
10197.91576.747610230.05583.422710313.92594.712310325.81596.937310342.48601.4433
#Mann= 3 , 0 , 0
9731.749    0.12       09731.749    0.12       010342.48    0.12       0
#XS Ineff= 2 , 0
       0                               0
Bank Sta=9731.749,10342.48
Exp/Cntr=0.3,0.1

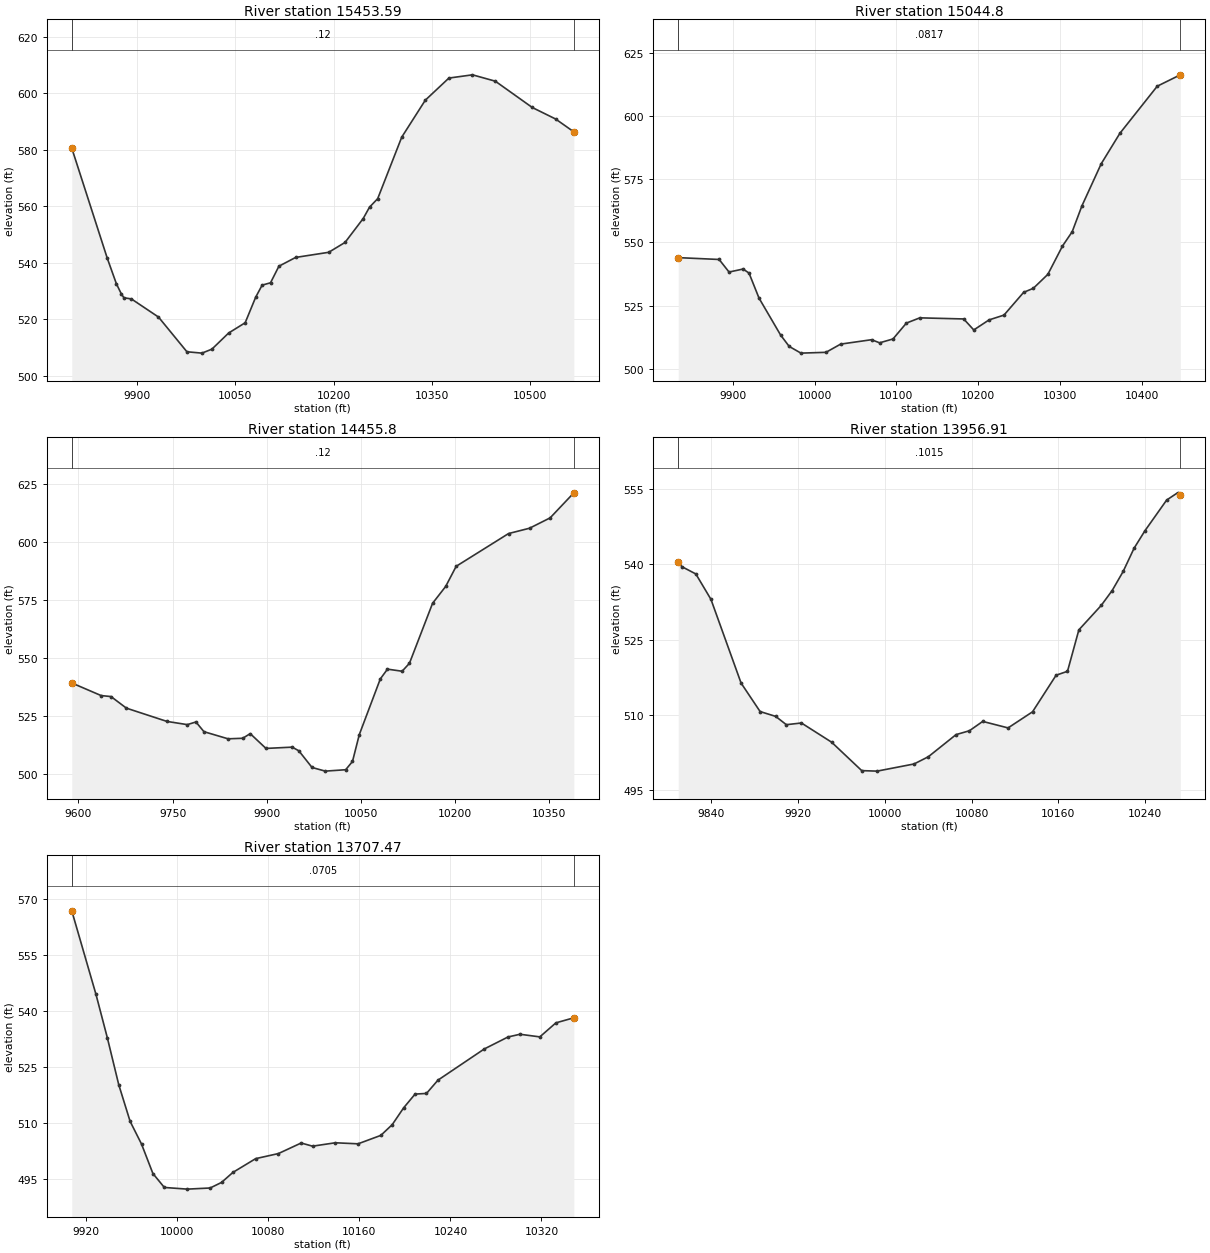
Type RM Length L Ch R = 1 ,15453.59,408.784100,408.784100,408.784100
XS GIS Cut Line= 6
 484442.45453928802458.593908446484423.266610484802403.274530703
 484401.78077261802364.501571509484170.694864481 802059.98717767
484099.420228614801952.384246415484025.670275476801820.141561132
#Sta/Elev= 30
9800.467580.56219854.656541.57029868.597532.52169876.192528.9242 9880.03527.6022
9891.463527.19659932.768520.78069976.126508.5024    9999 508.02110014.19509.4176
10039.76515.1325   10065518.768910081.06527.822910090.89532.079510103.68532.9099
10116.46538.774210142.03 541.88310192.43543.693910217.34547.186510245.06555.6477
10254.69559.667710267.15562.670510303.82584.4316 10339.8597.515910375.79605.3398
10411.77606.485910446.62604.232510502.97594.927410538.51590.864210566.39586.3059
#Mann= 3 , 0 , 0
9800.467    0.12       09800.467    0.12       010566.39    0.12       0
#XS Ineff= 2 , 0
       0                               0
Bank Sta=9800.467,10566.39
Exp/Cntr=0.3,0.1

Type RM Length L Ch R = 1 , 15044.8,588.998900,588.998900,588.998900
XS GIS Cut Line= 6
 484752.84901842802170.160381945484740.619624699802140.095403927
484730.431903072802122.809585172484519.841367579 801838.73665383
484462.122385482801748.916466502484413.047183029801660.322895109
#Sta/Elev= 30
9833.127543.98149883.183543.25249895.279538.28049912.513539.46889919.747537.8606
9931.981527.95459958.393513.33859968.887  508.849983.269 506.18610013.92506.5068
10031.82509.752510069.67 511.49810079.51510.2627 10095.9511.7925 10112.3518.0804
 10128.7520.150210182.41519.710810194.73515.355510213.44519.337510231.68 521.234
10255.73530.234910267.62 531.84910285.35537.357510303.28548.569610315.16554.2355
10327.05564.470310350.64581.123610373.51593.181910419.23611.833210447.44616.3335
#Mann= 3 , 0 , 0
9833.127  0.0817       09833.127  0.0817       010447.44  0.0817       0
#XS Ineff= 2 , 0
       0                               0
Bank Sta=9833.127,10447.44
Exp/Cntr=0.3,0.1

Type RM Length L Ch R = 1 , 14455.8,498.891400,498.891400,498.891400
XS GIS Cut Line= 6
484804.803572327802101.131748468484896.822535753801995.261859372
484935.391385287801975.327198893485012.466180205801871.207704425
485181.003995389801799.213344008485425.249115169801622.667114004
#Sta/Elev= 30
9589.351539.04419636.148533.6056 9651.85 533.181 9676.37528.18619740.822522.4688
9773.407521.07549787.105522.22679799.914518.03189838.316514.95919861.651515.1928
9873.592517.19219898.665510.81479940.514511.36849951.021509.78859972.034502.6017
9993.123501.023210025.61501.625310036.48 505.18610047.34516.7852 10080.8540.7897
10092.19545.004510115.54544.103410127.22547.537810164.04573.407110184.95580.6909
10201.63589.362110285.06603.482910318.43605.776710351.28610.243110389.06621.0468
#Mann= 3 , 0 , 0
9589.351    0.12       09589.351    0.12       010389.06    0.12       0
#XS Ineff= 2 , 0
       0                               0
Bank Sta=9589.351,10389.06
Exp/Cntr=0.3,0.1

Type RM Length L Ch R = 1 ,13956.91,249.445800,249.445800,249.445800
XS GIS Cut Line= 6
484782.074356149802137.630659145484931.141392643802284.991950512
484990.130153612802330.764805074 485072.86400036802366.907157981
485111.403519271802373.350496563485157.561147764802372.748198907
#Sta/Elev= 30
9809.428540.46639812.804539.51519825.672538.06119839.579533.01119867.393516.3237
 9884.93510.6526 9899.32509.68369909.114508.03219923.021508.37189950.835504.5525
9978.649498.88049992.817498.780910026.88500.205410040.05501.643110065.64506.0573
10077.93506.822110090.22508.685310113.61507.391610136.18510.600910157.92517.8942
10168.41518.6695 10178.9526.929610199.46531.7799 10209.6534.761210219.74538.5632
10229.83543.196310239.84546.676210259.86552.789710269.88554.227810272.45553.8844
#Mann= 3 , 0 , 0
9809.428  0.1015       09809.428  0.1015       010272.45  0.1015       0
#XS Ineff= 2 , 0
       0                               0
Bank Sta=9809.428,10272.45
Exp/Cntr=0.3,0.1

Type RM Length L Ch R = 1 ,13707.47,249.445700,249.445700,249.445700
XS GIS Cut Line= 6
484703.778019909802477.702110368484755.702467904802475.523073574
484822.347180353 802481.68081903484966.463485934802482.029965862
485068.768188046802468.743574674485139.463612079 802444.22004998
#Sta/Elev= 30
9907.154566.95439928.434 544.5199938.437532.8394 9948.44520.27499958.443510.4223
9968.451504.3467 9978.46496.43069988.515492.685710008.69492.236510028.78492.5416
10038.78494.031410048.78496.724610068.78500.420610088.78501.785110108.78504.6182
10118.78503.770210138.78504.679510158.78504.401510178.81506.666410188.84509.5539
10198.88514.071110208.91517.752210218.94517.928310229.01521.493210269.73529.8669
10290.61533.088810301.11533.815210318.55533.111510332.69536.877510348.46538.2345
#Mann= 3 , 0 , 0
9907.154  0.0705       09907.154  0.0705       010348.46  0.0705       0
#XS Ineff= 2 , 0
       0                               0
Bank Sta=9907.154,10348.46
Exp/Cntr=0.3,0.1