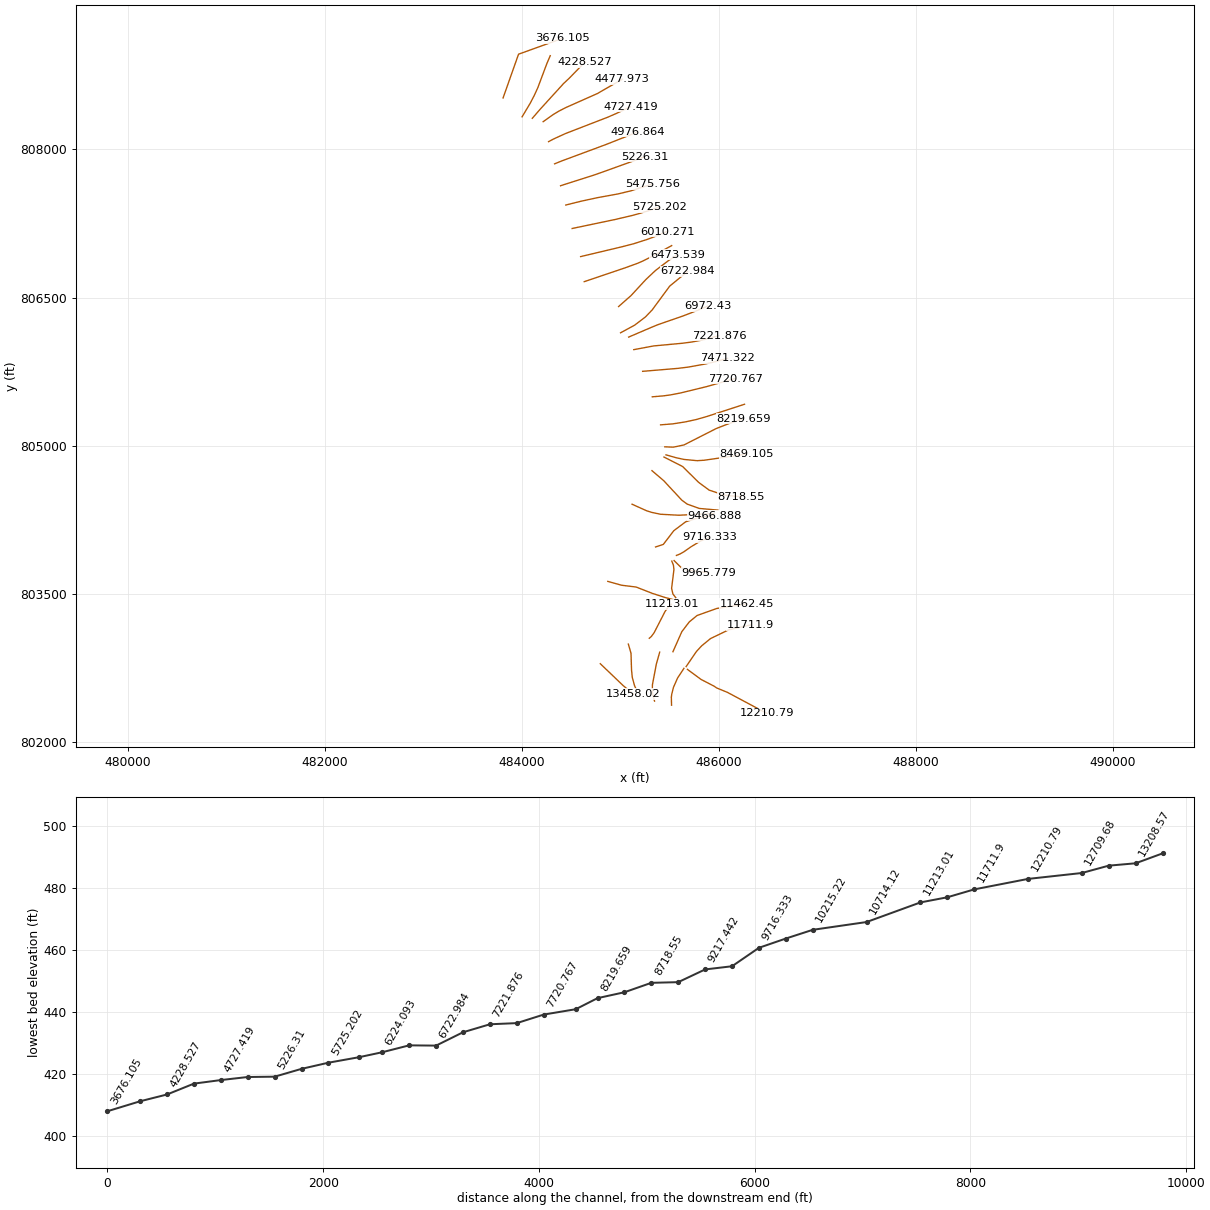
HEC-RAS study 5528_ras.prj: 5528

--- 5528_ras.g01 (geometry) --- (continued)

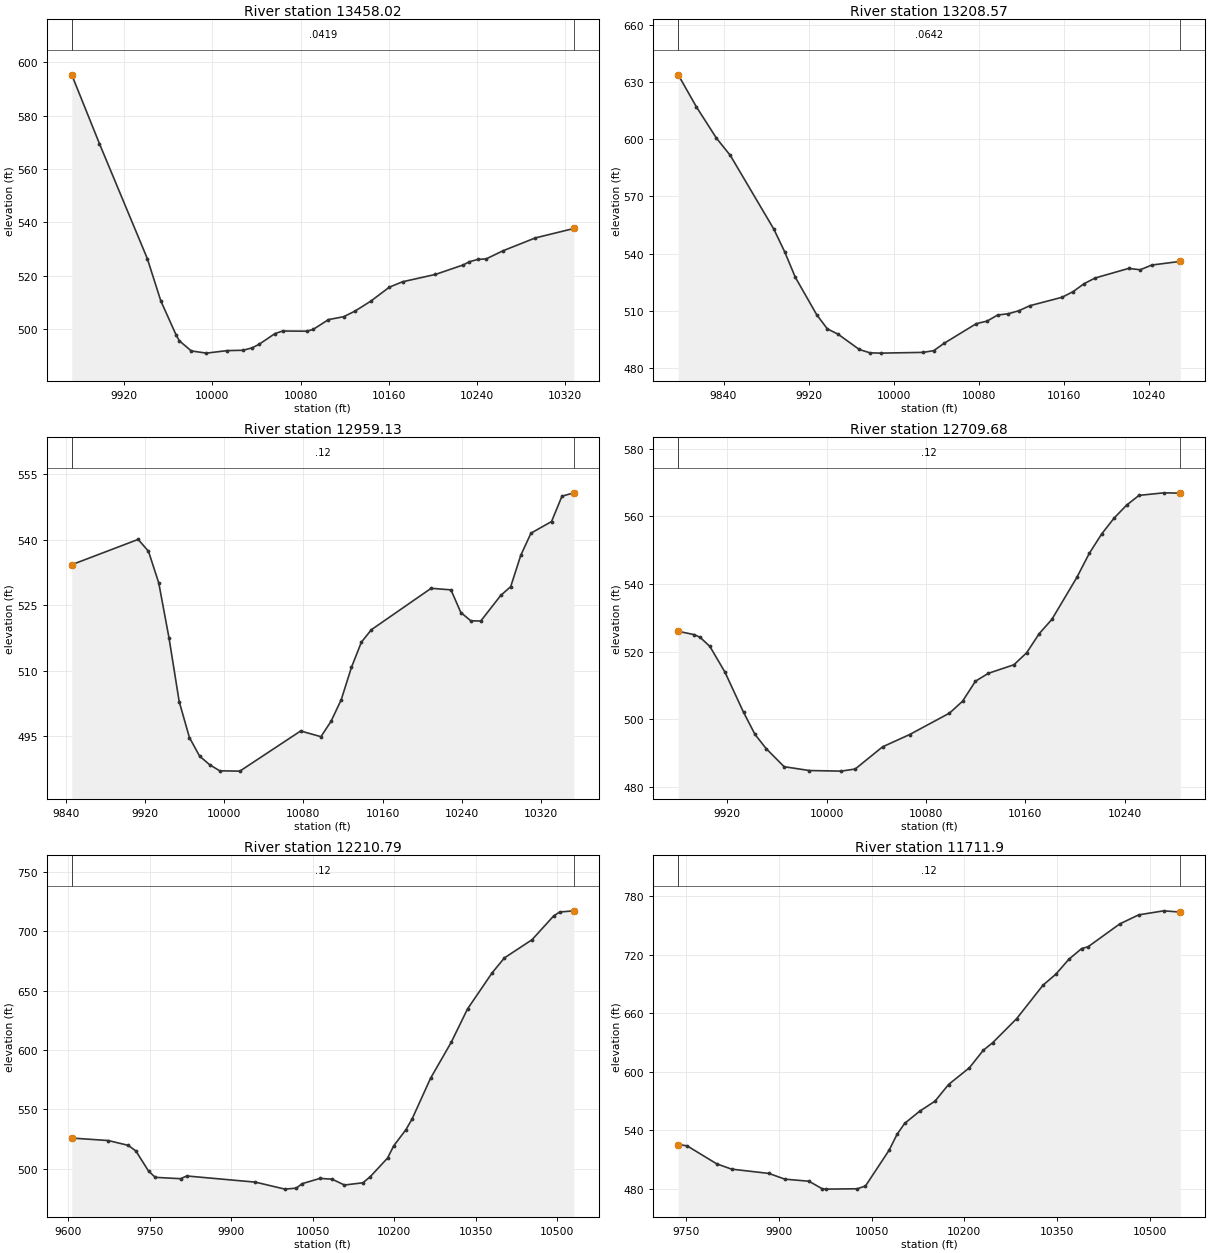
Type RM Length L Ch R = 1 ,13458.02,249.445800,249.445800,249.445800
XS GIS Cut Line= 6
 484796.49967467802792.293439038484888.141005297802704.973934756
484889.590121892 802703.59550772485024.197771549802574.931379851
485089.758634609 802518.63585837485132.388380087802484.902633831
#Sta/Elev= 30
9872.419 595.2999897.488569.55179940.977526.43639953.223 510.5759967.036497.8736
 9969.97495.66079980.849 491.8379994.661 491.01310013.44 491.95710027.91492.0877
10036.15493.003810042.38494.319710056.86498.358110063.82499.2974 10085.8499.2291
10091.48499.911510105.32503.567510119.15504.672110129.22506.719210143.69510.4746
10160.65515.752310172.64517.760110202.45520.511910227.81524.093510233.15525.2579
10240.99526.1302 10248.5526.340110263.85529.395910293.06534.189110327.98537.7205
#Mann= 3 , 0 , 0
9872.419  0.0419       09872.419  0.0419       010327.98  0.0419       0
#XS Ineff= 2 , 0
       0                               0
Bank Sta=9872.419,10327.98
Exp/Cntr=0.3,0.1

Type RM Length L Ch R = 1 ,13208.57,249.445700,249.445700,249.445700
XS GIS Cut Line= 6
485081.430460333802990.763130438485108.458781896802898.063818013
485113.950645311802726.371957907485121.763541647802652.188306814
485144.262273525802569.936104034485162.547321472802530.794646184
#Sta/Elev= 30
9797.395633.71799814.488616.92029833.363600.48259846.324591.50089887.288552.8243
9897.422541.00899907.475527.60919927.581 507.9619937.615500.53799947.617497.7884
 9967.62489.74879977.621487.98649987.623487.825810027.63488.219710037.63489.1317
10047.63493.068110077.66503.282810087.69504.593710097.72 507.80710107.76508.4714
10117.85510.096510127.95512.6788 10158.5517.144610168.74520.098610178.99524.2219
 10189.3527.196910220.93532.247410231.72531.528110242.75534.012310269.47535.9167
#Mann= 3 , 0 , 0
9797.395  0.0642       09797.395  0.0642       010269.47  0.0642       0
#XS Ineff= 2 , 0
       0                               0
Bank Sta=9797.395,10269.47
Exp/Cntr=0.3,0.1

Type RM Length L Ch R = 1 ,12959.13,249.445700,249.445700,249.445700
XS GIS Cut Line= 6
 485399.93021319802909.294595072485365.846855349802788.907156963
485326.033082406802579.839188877485324.817760976802520.441600228
485330.823405322802471.209123089 485347.41317321802413.667926574
#Sta/Elev= 30
9846.191534.30749913.235540.09439923.663537.37689934.028530.13689944.362517.5874
9954.696 502.9589965.029494.73949975.298490.49529985.465488.52289995.631487.1305
10015.93487.060410077.34496.250510097.84494.942310108.09498.488310118.35503.4261
10128.58510.778110138.67516.578710148.77519.425610209.12528.901810229.13528.5449
10239.13523.356310249.17521.467310259.25521.419210279.39 527.26510289.47529.2861
10299.67536.474710309.95541.519610330.72 544.18510341.24549.981710353.24550.7529
#Mann= 3 , 0 , 0
9846.191    0.12       09846.191    0.12       010353.24    0.12       0
#XS Ineff= 2 , 0
       0                               0
Bank Sta=9846.191,10353.24
Exp/Cntr=0.3,0.1

Type RM Length L Ch R = 1 ,12709.68,498.891500,498.891500,498.891500
XS GIS Cut Line= 6
 485645.79105258802745.247632033485580.769695025802646.356756144
485539.292665493802552.075550399485522.131610059802483.550086744
485518.091617043 802451.38678864485520.261746161802371.896188125
#Sta/Elev= 30
9880.505526.00489893.478525.02149898.104524.2288 9906.02521.53029918.128513.9495
9933.108502.08679942.345495.54119951.362 491.3369965.811486.00369986.087484.8693
 10011.8 484.69310023.04485.317510045.07491.863810066.97495.5147   10099501.8324
 10109.5505.337710119.93511.272510130.37 513.60110150.87 516.114 10161.1519.6433
10171.33525.343410181.43529.506810201.59541.927710211.62549.046110221.63554.7921
10231.63559.466810241.64563.278110251.65566.163210271.72566.921310284.93566.8265
#Mann= 3 , 0 , 0
9880.505    0.12       09880.505    0.12       010284.93    0.12       0
#XS Ineff= 2 , 0
       0                               0
Bank Sta=9880.505,10284.93
Exp/Cntr=0.3,0.1

Type RM Length L Ch R = 1 ,12210.79,498.891500,498.891500,498.891500
XS GIS Cut Line= 6
485681.086100429802734.907566831485819.845143288802633.006394729
485952.151651085802564.659565624485977.985622608802547.097054788
486087.669562726802501.907196875 486488.14455846 802289.34847141
#Sta/Elev= 30
9606.197525.78839673.619523.68389710.308519.62959724.302514.88299747.529498.0438
9759.936492.71149806.667491.55799817.922493.86499944.452488.66559998.698482.7873
10019.76483.624910030.32487.375510063.42491.8301 10085.7491.138110108.36486.2418
10142.35488.136210155.92493.273110187.67508.9203   10199519.192610221.66532.9077
10232.99541.946910266.97576.193610304.84606.287710334.95634.449310380.27664.8754
10402.93677.457710453.76692.752810493.53712.756810504.77716.102110530.79717.0908
#Mann= 3 , 0 , 0
9606.197    0.12       09606.197    0.12       010530.79    0.12       0
#XS Ineff= 2 , 0
       0                10087.41       0
Bank Sta=9606.197,10530.79
Exp/Cntr=0.3,0.1

Type RM Length L Ch R = 1 , 11711.9,249.445700,249.445700,249.445700
XS GIS Cut Line= 6
485668.077440172802763.092997402485771.222172916802913.801364616
485826.034793496802973.359286845485916.338778406803047.010497957
486100.582993239803135.440650046486321.551340312803184.508239582
#Sta/Elev= 30
9737.288525.19569751.582 523.8759799.599505.34769823.608499.93559883.884 495.528
9909.755489.64579948.663487.52379970.327479.70689975.662479.405910026.59479.7718
10040.09482.603610078.49519.562410090.98535.504710103.48546.924510127.76559.4257
10152.55569.735910174.44586.837910208.27604.081110230.48621.924510245.81629.7672
10284.53654.442810327.19688.813310348.03700.165310368.87715.3569 10389.7726.4579
10399.98728.2255 10451.2751.684210481.82761.023410522.34  765.1710549.23763.8775
#Mann= 3 , 0 , 0
9737.288    0.12       09737.288    0.12       010549.23    0.12       0
#XS Ineff= 2 , 0
       0                               0
Bank Sta=9737.288,10549.23
Exp/Cntr=0.3,0.1

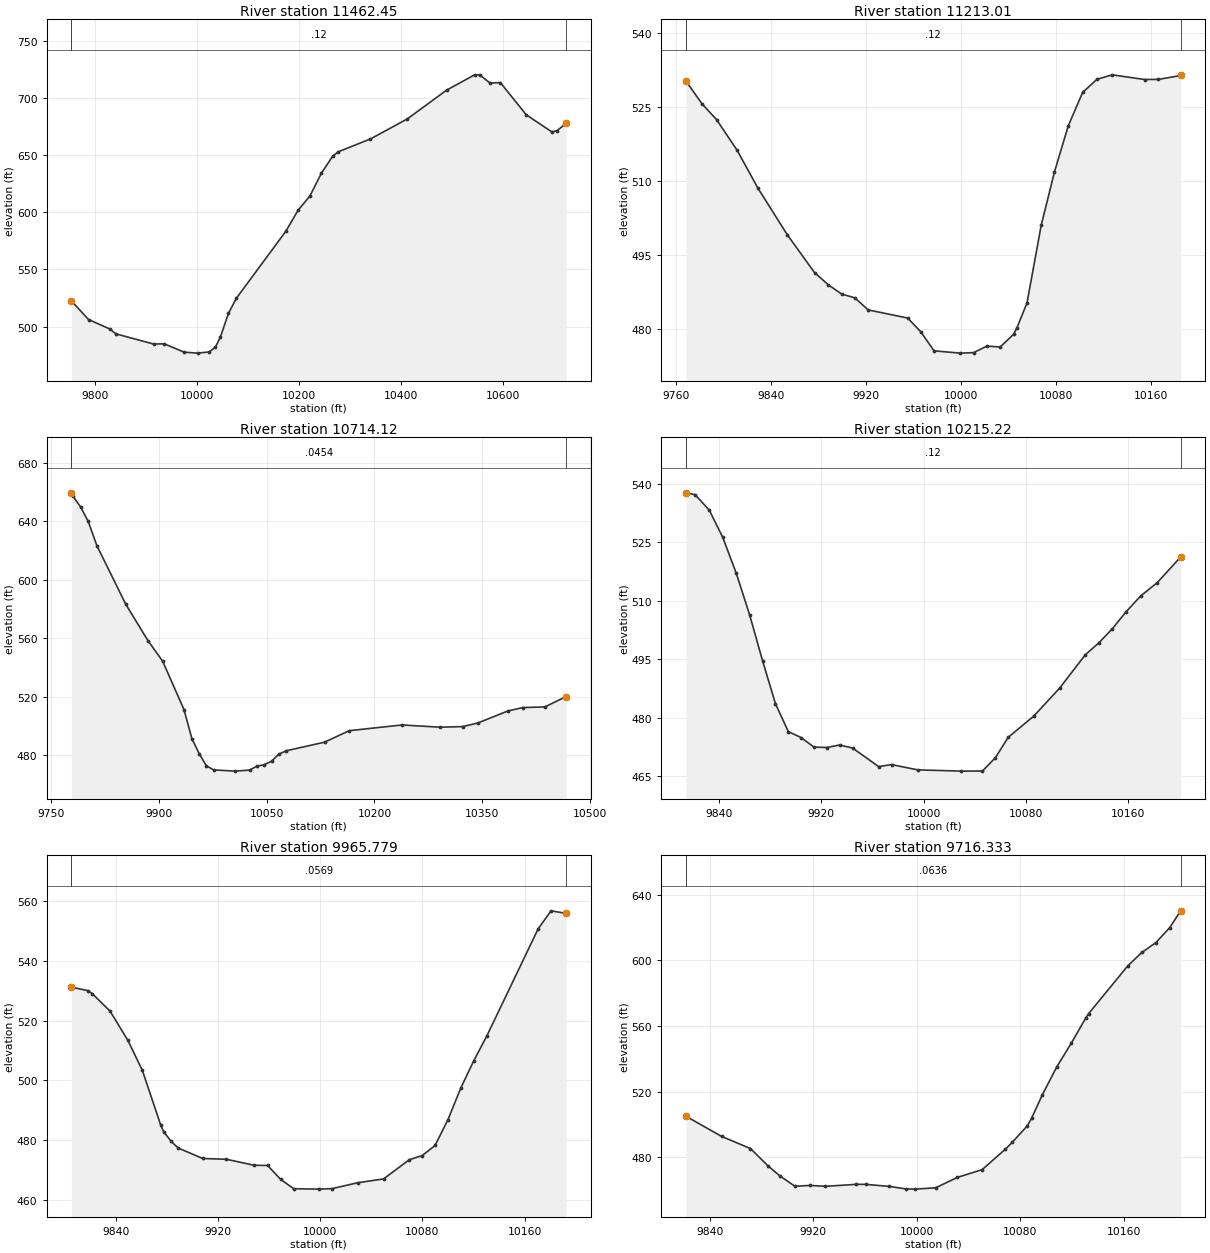
Type RM Length L Ch R = 1 ,11462.45,249.445800,249.445800,249.445800
XS GIS Cut Line= 6
485534.327819139802913.664330561485624.356529476803116.332730289
485700.451803012 803215.69901763485779.182614037803280.313123651
485978.783591093803351.326109531486282.701761479803398.180923185
#Sta/Elev= 30
9753.526522.48499787.211506.17869829.377497.87519840.339493.76799914.751484.7933
 9935.66 485.0079974.615477.7241   10001476.863910023.47477.877510035.86481.9572
10045.74490.870410061.55511.598910077.13524.814410173.96 583.24810198.39 601.837
10221.32614.160410243.86634.061210265.99648.891910276.65652.775210340.16 664.047
10412.39681.532610489.63706.729710544.57720.080910554.68719.965310574.89712.9078
 10595.1713.247810645.62685.211410696.04670.1949 10706.1671.3138 10723.9677.5844
#Mann= 3 , 0 , 0
9753.526    0.12       09753.526    0.12       0 10723.9    0.12       0
#XS Ineff= 2 , 0
       0                               0
Bank Sta=9753.526,10723.9
Exp/Cntr=0.3,0.1

Type RM Length L Ch R = 1 ,11213.01,498.891400,498.891400,498.891400
XS GIS Cut Line= 6
485294.183100596803050.027441926 485313.97396869803066.330321339
485344.003165988803107.390945768485455.201153172803323.048771368
485486.694796977  803365.6433821485519.886465798803394.300419039
#Sta/Elev= 30
9768.419  530.259782.042 525.6349794.188522.45989811.384516.29679829.038508.5628
9853.801499.12719876.623491.50819888.033489.06259899.444 487.1639910.648486.3845
 9921.74483.95169955.017482.30829966.109  479.519977.201475.66449999.385475.2024
10010.56475.304610021.75476.628210032.94476.444210044.13479.0054 10047.1480.3844
10055.49485.375910067.43 501.08110078.57511.867410090.22521.217910102.31527.9766
 10114.4530.630310127.15531.536310154.46530.590310166.15530.612710184.84531.4003
#Mann= 3 , 0 , 0
9768.419    0.12       09768.419    0.12       010184.84    0.12       0
#XS Ineff= 2 , 0
       0                               0
Bank Sta=9768.419,10184.84
Exp/Cntr=0.3,0.1

Type RM Length L Ch R = 1 ,10714.12,498.891500,498.891500,498.891500
XS GIS Cut Line= 6
484872.792519293803625.636799974485014.426811031803586.497898137
485160.757902225803568.485534516485324.692265011803504.534148506
485454.818379726803462.563059361485533.646720756803442.373085208
#Sta/Elev= 30
9777.955659.57589780.268 657.1629790.748649.92679801.228640.12279813.512623.3158
9853.619 583.2659884.458558.38359905.017 544.2049934.723511.08639945.809491.0464
9955.929480.8705 9966.05472.4613 9976.17469.698410006.22468.881410026.26469.6024
 10036.3 472.32710046.49473.229810056.67475.686510066.85480.547510077.19482.8283
10130.63 488.73510164.83496.592210238.39500.515710291.11498.983910322.63499.3884
10343.64501.803910385.67510.071410406.32512.422110437.28512.875610466.86519.9648
#Mann= 3 , 0 , 0
9777.955  0.0454       09777.955  0.0454       010466.86  0.0454       0
#XS Ineff= 2 , 0
       0                               0
Bank Sta=9777.955,10466.86
Exp/Cntr=0.3,0.1

Type RM Length L Ch R = 1 ,10215.22,249.445700,249.445700,249.445700
XS GIS Cut Line= 6
485522.501058139803831.250389286485539.278457703803789.658826376
485544.379238627803745.704939027485520.736282971803554.577963179
 485533.93696948803498.087805076485562.278739534803462.195252057
#Sta/Elev= 30
9814.185537.72559821.243537.2593 9832.36533.29949842.933526.30599853.505517.0769
9863.879506.50229874.025494.69749884.161483.63829894.173476.51329904.186474.9814
9914.207 472.5329924.227472.42879934.256473.06859944.427472.29739964.769 467.536
9974.941468.04819995.283 466.69810029.54466.373210045.98466.402210056.06469.8052
10066.09475.0438 10086.1480.4908 10106.2487.6286 10126.4496.2178 10136.9 499.247
10147.48502.872310158.33507.256210169.79511.333110182.48514.658310200.93521.2889
#Mann= 3 , 0 , 0
9814.185    0.12       09814.185    0.12       010200.93    0.12       0
#XS Ineff= 2 , 0
       0                               0
Bank Sta=9814.185,10200.93
Exp/Cntr=0.3,0.1

Type RM Length L Ch R = 1 ,9965.779,249.445800,249.445800,249.445800
XS GIS Cut Line= 6
485546.045457256803836.547879093485615.841190841803767.563947753
485635.510971737803754.274032223485660.624923805803743.932480591
485685.782546471803738.934247145485896.645092213803713.613149807
#Sta/Elev= 30
9805.376 531.1969818.146530.04569821.574529.07589835.601523.18899849.627513.3521
9860.927503.30899875.187485.11479877.681482.73839883.486479.52889889.069477.3117
9908.127473.8237 9926.67473.56179948.363471.55719958.907471.47779969.102466.8439
9979.298463.70519999.416463.563110009.46  463.7410029.56465.714410049.65466.9772
10069.81473.408310079.89474.797910089.98478.186110100.06 486.84110110.15497.4705
10120.24506.554710130.32514.729910170.67550.755810180.75556.7633 10192.5555.9062
#Mann= 3 , 0 , 0
9805.376  0.0569       09805.376  0.0569       0 10192.5  0.0569       0
#XS Ineff= 2 , 0
       0                               0
Bank Sta=9805.376,10192.5
Exp/Cntr=0.3,0.1

Type RM Length L Ch R = 1 ,9716.333,249.445700,249.445700,249.445700
XS GIS Cut Line= 6
485569.421182503803888.561622454485604.104260725803902.429626554
485642.974738027803923.764254986485716.632047165803975.353121873
485809.684436663804031.743505147485902.964480215804071.895698901
#Sta/Elev= 30
9821.711504.99949849.196492.72099871.565485.29399885.262474.6374 9894.38468.5762
9905.867462.33939917.667462.82489929.468462.29829953.308463.48399960.579 463.481
9978.739 462.2329991.455460.7461    9999460.574410014.66461.384810031.46467.7164
10050.59472.451610068.53484.900110074.02489.218210085.53499.164610088.77503.6994
10097.03517.901810108.32535.148110119.43549.414410130.55564.708510132.82567.4735
10163.26 596.73210174.02604.803710184.93 610.86510195.54619.947110204.05630.2017
#Mann= 3 , 0 , 0
9821.711  0.0636       09821.711  0.0636       010204.05  0.0636       0
#XS Ineff= 2 , 0
       0                               0
Bank Sta=9821.711,10204.05
Exp/Cntr=0.3,0.1

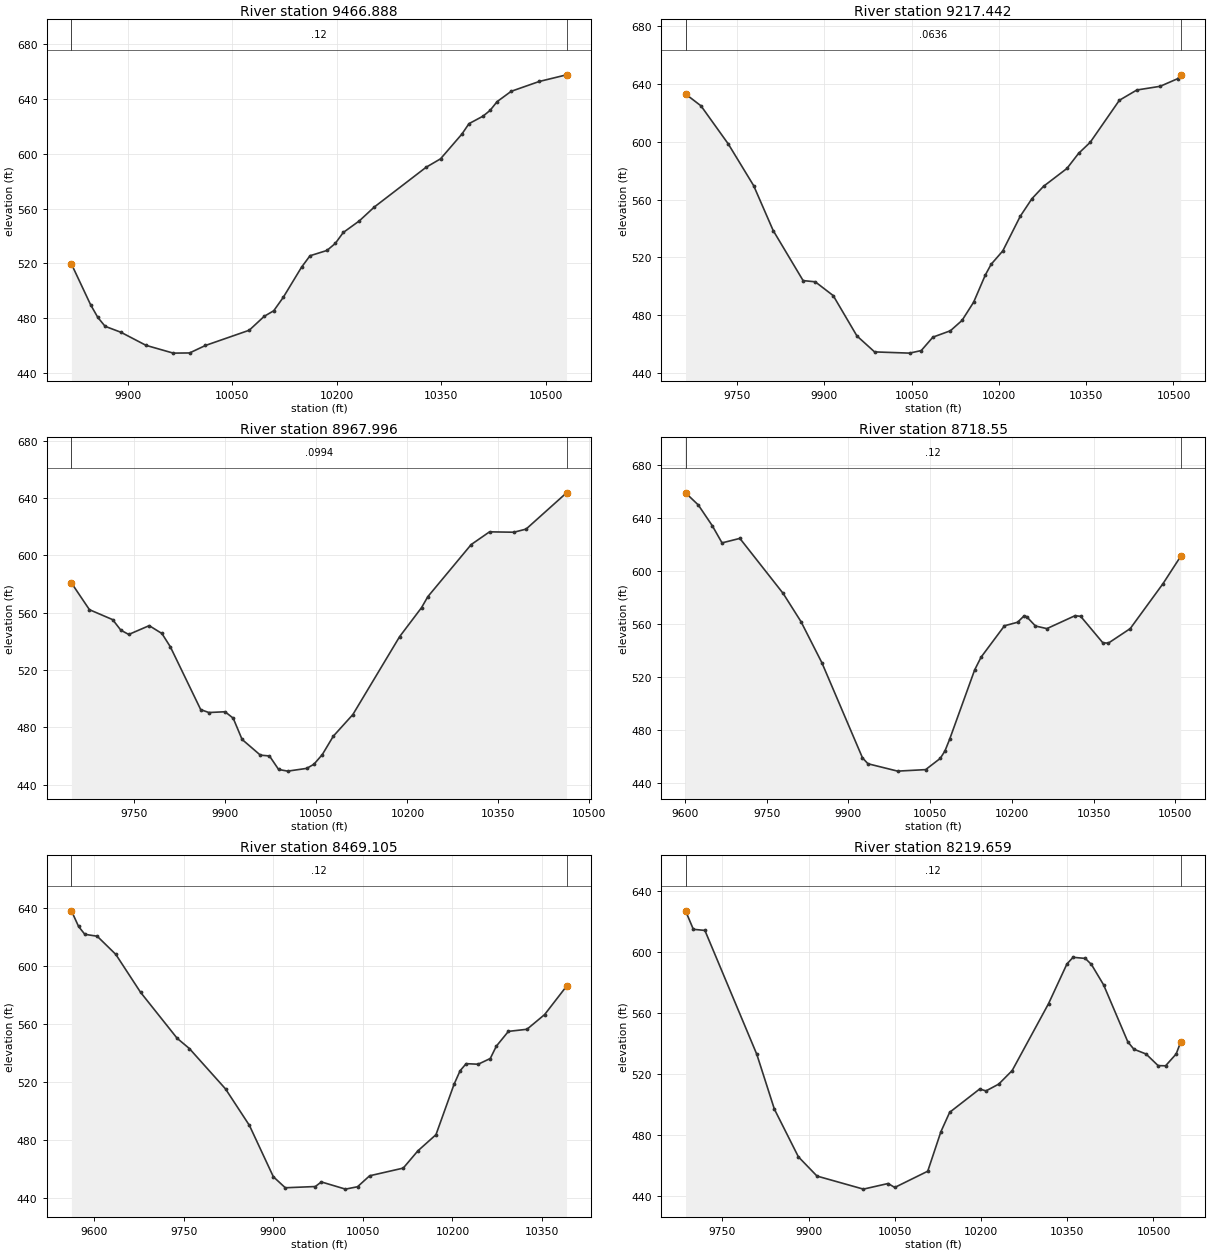
Type RM Length L Ch R = 1 ,9466.888,249.445800,249.445800,249.445800
XS GIS Cut Line= 6
485357.723163364803974.313834112485436.623975159804000.335960216
485543.333602301804139.111970297485663.402114572804228.979947809
485807.537356732804275.213668736485954.155073761  804291.7712334
#Sta/Elev= 30
 9818.96519.64919846.368490.04579856.861480.66379867.354474.17379890.039469.8389
9926.095460.29879965.215454.62379988.679454.757710011.45460.2161 10074.3471.3152
10095.84 481.47210109.47485.503410123.11495.248910149.42517.281210161.57525.6211
10185.89529.481910197.85 534.59910209.34542.596610232.23550.977510253.96561.1716
10328.45590.202410349.04596.299510379.74614.370710389.88621.939310410.08627.4261
10420.18631.624110430.28638.008910450.49 645.53410490.67652.687410529.96657.5477
#Mann= 3 , 0 , 0
 9818.96    0.12       0 9818.96    0.12       010529.96    0.12       0
#XS Ineff= 2 , 0
       0                               0
Bank Sta=9818.96,10529.96
Exp/Cntr=0.3,0.1

Type RM Length L Ch R = 1 ,9217.442,249.445700,249.445700,249.445700
XS GIS Cut Line= 6
485119.204102949804407.050789448485266.756022621804340.918470665
485316.577857142804324.953012812485407.618675638804305.595075339
 485593.23569864804295.664391468485950.227630139804312.717599367
#Sta/Elev= 30
9661.622633.16589688.157624.96049735.025598.56579778.644569.66559812.199538.5589
9863.611503.86379884.445503.02549915.348 493.4689956.099465.50939986.392454.4506
10046.57453.5978 10066.6455.379910086.63464.676110116.65 469.09310136.65476.2492
10156.65488.924710176.67507.720410186.67515.156110206.68524.432410236.73548.4582
10256.77560.6298 10276.8569.226810316.87581.5545 10336.9592.004110356.94599.7029
10407.02628.830810437.05635.944910477.07638.504910507.09643.766910512.32646.4599
#Mann= 3 , 0 , 0
9661.622  0.0636       09661.622  0.0636       010512.32  0.0636       0
#XS Ineff= 2 , 0
       0                               0
Bank Sta=9661.622,10512.32
Exp/Cntr=0.3,0.1

Type RM Length L Ch R = 1 ,8967.996,249.445700,249.445700,249.445700
XS GIS Cut Line= 6
485321.246032443 804746.96769821485441.522340543804644.639483275
485624.354311096804448.204554839485679.243698136804408.058689464
485801.959283276804364.412049407 485991.61210279804347.623713206
#Sta/Elev= 30
 9646.26580.76959675.966562.09629714.233555.16149727.675547.83149740.723544.8175
9774.453550.97359795.401 545.4949809.296536.21439859.359492.39499872.739490.3738
9899.499490.90719912.879486.42659927.542471.61149957.645460.65469972.696460.0729
9987.748450.647910002.73449.4962 10034.1451.414510045.97454.310210059.82461.0862
10077.87473.864310110.09488.943210187.15543.280410223.33563.548310233.69 571.195
10305.12607.524210335.38616.402610375.56616.1317 10395.6618.307810462.28643.6101
#Mann= 3 , 0 , 0
 9646.26  0.0994       0 9646.26  0.0994       010462.28  0.0994       0
#XS Ineff= 2 , 0
       0                               0
Bank Sta=9646.26,10462.28
Exp/Cntr=0.3,0.1

Type RM Length L Ch R = 1 , 8718.55,249.445800,249.445800,249.445800
XS GIS Cut Line= 6
485443.543856471804884.552750262485632.267411137804789.009004975
485794.786680008804628.669911385485902.093306378804549.783550126
486059.667709516 804497.91573778486227.461719129 804483.60125498
#Sta/Elev= 30
9600.838658.8226 9624.23649.69489649.926634.07339667.839621.13699700.598624.5143
9780.131583.0422 9812.81561.8636 9851.13530.95719925.787459.25789935.835454.8299
9990.294449.278710041.74450.412910068.46458.828610077.14464.418710085.74473.1919
10131.76525.493910143.54535.078210186.51 558.72110210.54561.370210222.21566.0417
10226.99 565.67910243.43558.548510264.43556.590710316.28 566.34110326.51565.7969
10367.05545.967510377.13545.620510417.44556.592310477.57590.399410510.06610.9652
#Mann= 3 , 0 , 0
9600.838    0.12       09600.838    0.12       010510.06    0.12       0
#XS Ineff= 2 , 0
       0                               0
Bank Sta=9600.838,10510.06
Exp/Cntr=0.3,0.1

Type RM Length L Ch R = 1 ,8469.105,249.445700,249.445700,249.445700
XS GIS Cut Line= 6
485463.545514124804907.054615112485567.777266218804877.565234749
485646.896248012 804860.51395319485778.359792946804848.021979715
485853.286460308804852.536634292486281.217285683804915.068433397
#Sta/Elev= 30
9561.934637.85149573.958627.06899584.338621.69359605.099620.36249636.241607.8602
9677.654581.77789739.031 550.0649759.387543.06149819.936515.24899859.993490.0979
9900.035 454.7719920.045447.18029970.305448.02379980.403451.195710020.81446.2398
10041.01447.879810061.22455.417710117.56460.722510142.03472.597410172.34483.7249
10202.65518.448710212.75527.749410222.85532.618110243.05532.239910263.26536.1745
10273.38 544.64310293.61554.849410324.68556.292510354.32566.443510390.96585.9357
#Mann= 3 , 0 , 0
9561.934    0.12       09561.934    0.12       010390.96    0.12       0
#XS Ineff= 2 , 0
       0                               0
Bank Sta=9561.934,10390.96
Exp/Cntr=0.3,0.1

Type RM Length L Ch R = 1 ,8219.659,201.602500,201.602500,201.602500
XS GIS Cut Line= 6
 485451.48218317804988.179582796485538.917748591804984.932665693
 485645.94711452805007.142356165 485976.46011031 805174.57093683
  486109.4738752805226.132523983486252.476174508805272.735595086
#Sta/Elev= 30
9686.121626.92569699.694614.79019719.774614.0694 9810.02532.82439840.621496.8293
9882.391465.52759914.776452.90629995.455444.337610038.48 448.02810049.96445.4352
10107.35456.0877 10130.3482.053310145.51494.736510197.69510.024110208.72508.7765
10230.86513.247510254.19522.111310317.43565.986910349.44592.0371 10360.1596.4321
10381.43595.699710392.09591.723510413.24578.368110455.44540.914910465.99536.1221
10487.09532.991810508.06 525.37210521.03525.245710539.46533.006310547.28540.8061
#Mann= 3 , 0 , 0
9686.121    0.12       09686.121    0.12       010547.28    0.12       0
#XS Ineff= 2 , 0
       0                               0
Bank Sta=9686.121,10547.28
Exp/Cntr=0.3,0.1

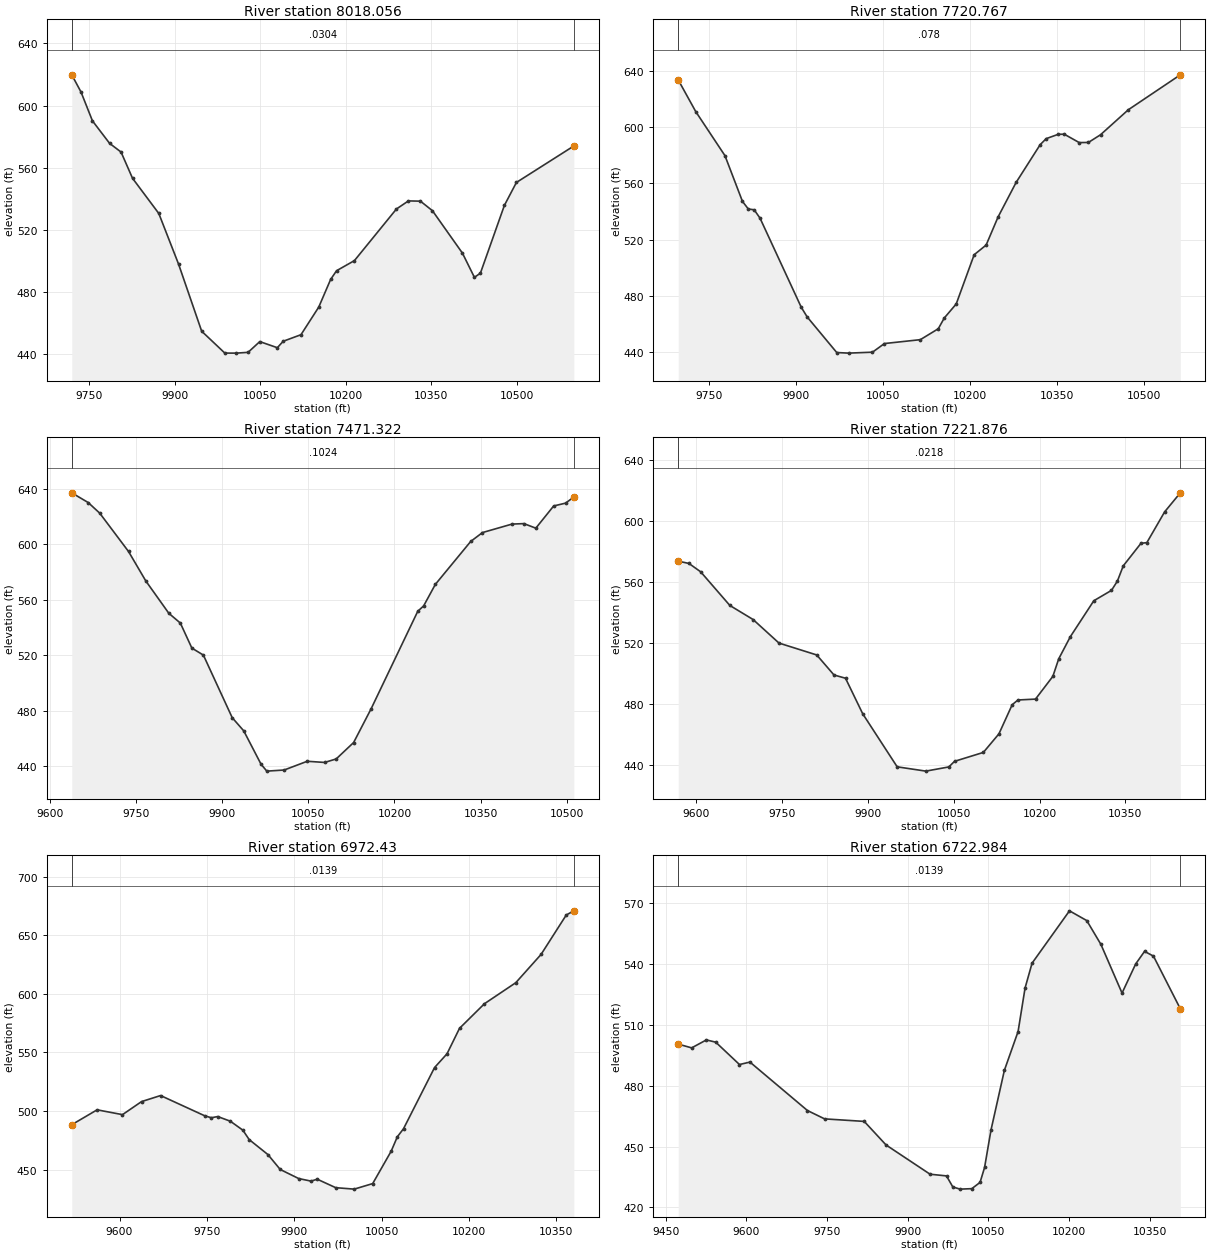
Type RM Length L Ch R = 1 ,8018.056,297.289000,297.289000,297.289000
XS GIS Cut Line= 6
 485408.81265891 805210.78799442485533.540343734805220.709800431
485660.708467295805240.807223318485772.378099226805264.927282943
485875.713727435805294.442666592486261.161987659 805419.21200558
#Sta/Elev= 30
 9719.19619.8355 9735.38608.79799755.442590.2315 9785.57575.73419805.656570.1465
9825.741553.29449871.844530.65399906.583498.00639947.079454.87529987.667440.8084
10008.04440.773110028.51 441.28210049.02448.1911 10079.8444.263810090.09448.4033
10121.29 452.62910152.49470.402510173.29488.176110183.69493.783510215.12500.3248
10288.77533.517710309.82538.718110330.86538.5471 10351.9532.413810404.51505.1257
10425.55489.528310436.07492.221510478.16535.8555 10499.2550.580510599.98574.0638
#Mann= 3 , 0 , 0
 9719.19  0.0304       0 9719.19  0.0304       010599.98  0.0304       0
#XS Ineff= 2 , 0
       0                               0
Bank Sta=9719.19,10599.98
Exp/Cntr=0.3,0.1

Type RM Length L Ch R = 1 ,7720.767,249.445700,249.445700,249.445700
XS GIS Cut Line= 6
 485324.87553995805494.606155618485439.456892166805504.320100281
485509.389337574805513.911586413  485611.3885233 805533.51784682
485873.374323582805597.110222979486166.877484703805679.948089625
#Sta/Elev= 30
9697.795633.75169727.965611.13419778.193579.7634 9808.33547.15879818.402541.7445
9828.496541.1738 9838.59535.19579909.474471.75669919.657464.84489970.572439.4606
9990.968439.039810032.11439.712410052.69445.871610114.44448.631710145.32456.4131
10155.61464.060110176.19474.072210207.07509.159610227.65516.038710248.24536.0849
10279.26560.678210320.71587.617210331.07591.8938 10351.8594.975410362.16595.0451
10387.88589.074610403.68589.169210424.51594.643110472.38612.473810561.84637.3609
#Mann= 3 , 0 , 0
9697.795   0.078       09697.795   0.078       010561.84   0.078       0
#XS Ineff= 2 , 0
       0                               0
Bank Sta=9697.795,10561.84
Exp/Cntr=0.3,0.1

Type RM Length L Ch R = 1 ,7471.322,249.445800,249.445800,249.445800
XS GIS Cut Line= 6
 485226.44507334805752.583368626485586.270183512805782.801762184
485691.738751575805795.819038218485862.687247068805826.787592576
485969.096547999805851.534506691 486088.90064399805884.173148599
#Sta/Elev= 30
9637.899637.0736 9666.54630.04919686.601622.40359736.752594.75459766.843573.5118
9806.964550.16959827.024543.11269847.087525.06069867.172519.98739917.385474.8446
9937.469465.33429967.597441.27889977.639436.288610007.77437.083810048.07443.3972
10078.32442.553310098.48445.074910128.85456.923410159.26481.2093 10240.6551.6297
 10250.8555.485610271.19571.013510332.74601.967910353.27608.400910404.76614.5229
10425.49614.858810446.22611.577510477.31627.594910498.04629.637910512.45634.0335
#Mann= 3 , 0 , 0
9637.899  0.1024       09637.899  0.1024       010512.45  0.1024       0
#XS Ineff= 2 , 0
       0                               0
Bank Sta=9637.899,10512.45
Exp/Cntr=0.3,0.1

Type RM Length L Ch R = 1 ,7221.876,249.445700,249.445700,249.445700
XS GIS Cut Line= 6
485136.625853569805972.141461395485338.572449177806009.803649759
485629.576028116806036.887468688485724.519889042806049.221001971
485831.209805769806069.361322192486001.281329435806113.652305723
#Sta/Elev= 30
9568.219573.87129586.984572.34869607.411566.87959658.477544.75699699.105535.5135
9744.404520.03879810.366512.23789840.571499.07679860.709496.94259890.842473.5534
9951.026 438.74110001.18435.914310041.33438.671610051.36442.359710101.71448.2054
10128.97460.418810152.13479.546410162.22482.654610192.89483.231410223.28498.1961
10233.46509.673410253.81524.234910294.83547.846210325.75554.672110336.05560.7547
10346.36570.781110377.28585.574310387.59586.034910418.64606.217410446.09618.7544
#Mann= 3 , 0 , 0
9568.219  0.0218       09568.219  0.0218       010446.09  0.0218       0
#XS Ineff= 2 , 0
       0                               0
Bank Sta=9568.219,10446.09
Exp/Cntr=0.3,0.1

Type RM Length L Ch R = 1 , 6972.43,249.445700,249.445700,249.445700
XS GIS Cut Line= 6
 485084.58255762806099.358407059485319.731735635806199.807442393
485385.943268352806226.584385723485633.745456226806312.230841899
485770.769504969806364.622869908485886.977040626806413.020681139
#Sta/Elev= 30
 9517.97 488.2889561.455500.97879605.051496.87219637.748508.00079670.445513.1569
9746.738 495.7679757.637494.23549768.536495.23699790.163 491.2789811.736483.6068
9822.523475.59699854.697462.8067 9875.86450.08349907.605442.34239928.767440.1647
9939.349441.80389971.093434.567910002.84433.332810034.57438.055610066.31465.7145
10076.89477.990210087.47484.842510140.76537.027110162.17548.783310183.59570.4828
10226.41591.489210280.25609.436610323.58633.529810366.91667.186210379.88670.7319
#Mann= 3 , 0 , 0
 9517.97  0.0139       0 9517.97  0.0139       010379.88  0.0139       0
#XS Ineff= 2 , 0
       0                               0
Bank Sta=9517.97,10379.88
Exp/Cntr=0.3,0.1

Type RM Length L Ch R = 1 ,6722.984,249.445800,249.445800,249.445800
XS GIS Cut Line= 6
 485002.29078608 806142.71376045485145.547172489806220.167250375
485254.967243052806303.303656924485323.048158037806373.873843561
 485501.18104327806615.212393129485682.394326961806763.617382773
#Sta/Elev= 30
9473.147500.38429498.136498.53179525.432502.43929542.876501.3401 9587.04490.3397
9606.558491.54129713.491467.70829745.409 463.597 9819.09462.35769859.724450.7548
9941.561436.37389972.124435.54029983.843430.11549997.263429.035810019.21429.2636
10034.56432.359710042.95439.695210054.89458.122810079.79487.501210105.28506.5721
10118.28527.996310131.28540.202210200.87565.9581   10233561.162810259.28 549.476
10298.63525.490810324.07539.853110340.53546.013810357.12543.660510407.02517.7745
#Mann= 3 , 0 , 0
9473.147  0.0139       09473.147  0.0139       010407.02  0.0139       0
#XS Ineff= 2 , 0
       0                               0
Bank Sta=9473.147,10407.02
Exp/Cntr=0.3,0.1

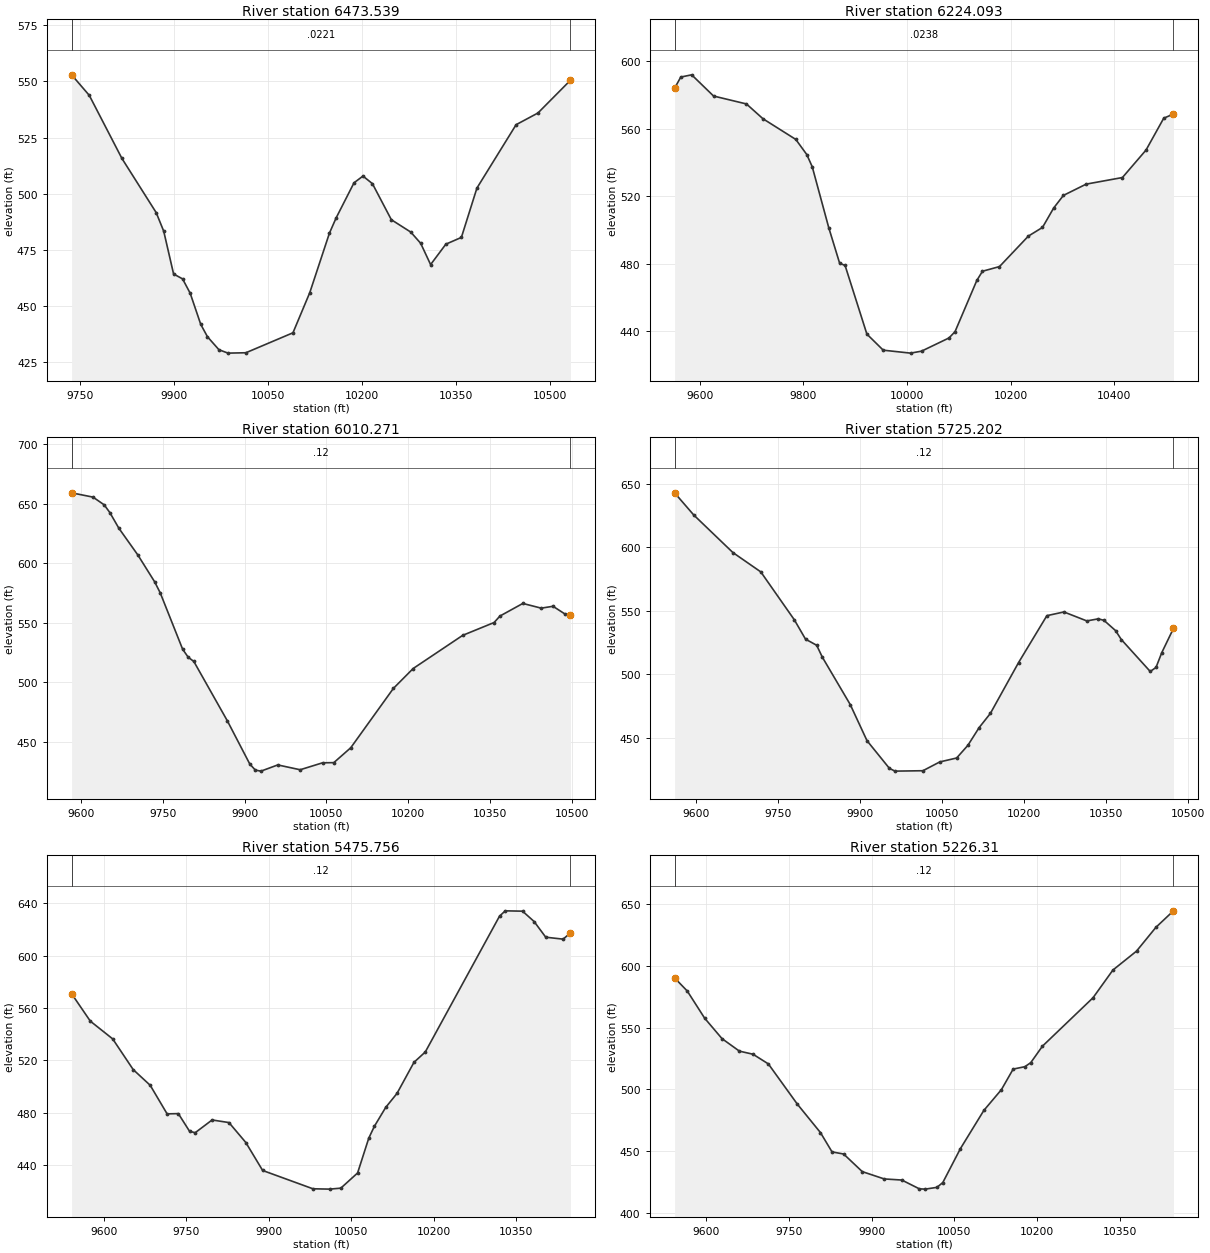
Type RM Length L Ch R = 1 ,6473.539,249.445700,249.445700,249.445700
XS GIS Cut Line= 6
484982.577774461806408.852694234 485107.92322048806518.743396411
485260.512411903806683.256447921485359.075675017806775.466938936
485489.726647723806874.235237552 485578.85089775806932.176453579
#Sta/Elev= 30
9736.876552.90079765.082543.76949817.146515.73219871.917491.60659883.937483.3429
9899.688464.31319914.016462.14359926.181455.75949943.037 441.9119953.782436.3914
9972.059430.6365 9986.57429.1173 10015.1429.283310090.26438.1606 10117.1456.0131
10148.48482.4753 10159.2489.280210187.74504.877710202.01 507.86910217.09504.4999
10247.35488.4506 10278.3482.964210294.15477.9689   10310468.495110334.35477.5766
10359.15480.584910383.96502.541710446.48530.717310481.37535.921910533.33550.5139
#Mann= 3 , 0 , 0
9736.876  0.0221       09736.876  0.0221       010533.33  0.0221       0
#XS Ineff= 2 , 0
       0                               0
Bank Sta=9736.876,10533.33
Exp/Cntr=0.3,0.1

Type RM Length L Ch R = 1 ,6224.093,213.822400,213.822400,213.822400
XS GIS Cut Line= 6
484633.615616405806660.418144827485050.075322455806801.074520499
485179.037015158806847.839982053485232.996487713806871.759792369
485308.686458019806909.660092533485521.460012362807025.603476316
#Sta/Elev= 30
9551.395584.06179563.376590.70369584.426592.02959626.667579.44849690.151574.7458
9721.894565.99369785.378  553.69 9806.54544.72779817.121537.43859848.863501.4289
9869.958480.25129880.475478.91469922.543438.19249954.094428.647510006.79426.9009
10027.95428.060510080.96435.895210092.63439.624810134.71470.034210145.64475.4864
10178.46478.254710234.18496.338610261.45501.488410283.02513.001410301.82520.4871
10345.71527.1725 10415.7531.092610461.26547.398510495.42566.288810514.17568.7696
#Mann= 3 , 0 , 0
9551.395  0.0238       09551.395  0.0238       010514.17  0.0238       0
#XS Ineff= 2 , 0
       0                               0
Bank Sta=9551.395,10514.17
Exp/Cntr=0.3,0.1

Type RM Length L Ch R = 1 ,6010.271,285.069100,285.069100,285.069100
XS GIS Cut Line= 6
484596.890419429806914.349271709485013.388439578807012.938367991
485136.522347306807044.757424673485273.295461233807088.394941419
 485352.65447888807117.956384603485474.633082543 807168.45237728
#Sta/Elev= 30
9582.363659.02919621.601655.43079642.193648.92569652.489 642.468  9669.1 629.276
9703.907606.83569734.719584.30879744.989575.02669786.072527.71249796.343 520.937
9806.614517.43719868.238467.47119909.321431.28479919.592 426.1439929.862425.3073
9960.675430.511310001.76 426.46610042.91432.297510063.52432.438810094.58444.9221
10172.88494.792510209.11511.474610300.07539.345810357.66550.105510368.37555.5416
10410.39566.134910444.13 562.17510465.78563.742210487.42557.340810497.85556.1766
#Mann= 3 , 0 , 0
9582.363    0.12       09582.363    0.12       010497.85    0.12       0
#XS Ineff= 2 , 0
       0                               0
Bank Sta=9582.363,10497.85
Exp/Cntr=0.3,0.1

Type RM Length L Ch R = 1 ,5725.202,249.445700,249.445700,249.445700
XS GIS Cut Line= 6
484510.933580368807198.914852307484946.897132781807289.980606789
485120.972257771807330.670873888485200.159449803807352.401109338
485278.818526773807376.437707455485394.999276029807416.460042754
#Sta/Elev= 30
9561.636642.85629596.642 625.4049668.135595.81029719.186 580.5439780.448  542.77
9800.869527.54519821.289522.70529831.499513.41079882.551476.00939913.182447.5343
9954.023425.75689964.233423.526110015.35423.844710046.15430.777510076.96433.8694
 10097.5443.858910118.04457.826110138.58469.006210189.97508.996610241.82546.0475
10272.97548.972710314.79541.899510335.71543.545610346.16  542.3410367.25534.2857
10377.81527.230610430.62502.062810441.18505.234810451.74516.925310473.04535.9798
#Mann= 3 , 0 , 0
9561.636    0.12       09561.636    0.12       010473.04    0.12       0
#XS Ineff= 2 , 0
       0                               0
Bank Sta=9561.636,10473.04
Exp/Cntr=0.3,0.1

Type RM Length L Ch R = 1 ,5475.756,249.445800,249.445800,249.445800
XS GIS Cut Line= 6
484446.280692697807436.415255961 484599.63257292807474.532565265
484768.416066624807511.145139007484980.600456101807549.659220694
485107.987014755807580.440150337485327.665503971807649.398497488
#Sta/Elev= 30
9541.083570.90589575.085549.97239615.829536.38529653.194512.89359684.055500.9394
9714.832479.07859735.297479.26719755.763465.71269765.995464.69139796.693474.4117
9827.391472.42489858.088457.17119888.664435.80859980.095421.810410010.58421.5417
10030.92 422.28910061.43433.888810081.77460.5074   10092469.593310112.57 483.995
10133.15494.718910164.01518.472710184.59526.376710319.67630.1982 10330.1634.2898
 10361.6634.025110382.69626.075310403.77614.1252 10435.4612.640110448.81617.4475
#Mann= 3 , 0 , 0
9541.083    0.12       09541.083    0.12       010448.81    0.12       0
#XS Ineff= 2 , 0
       0                               0
Bank Sta=9541.083,10448.81
Exp/Cntr=0.3,0.1

Type RM Length L Ch R = 1 , 5226.31,249.445700,249.445700,249.445700
XS GIS Cut Line= 6
484393.132794423807631.652433291484409.307472518807637.068520719
484736.675539141807741.186159802484826.808650603807772.920626307
485117.692808646807877.329680228 485247.59806673807926.388550624
#Sta/Elev= 30
 9542.86590.43379565.891579.76849597.371  557.739628.852541.12689660.333 530.996
9685.068528.47229712.801 520.6339765.269488.02959807.243464.8955 9828.23449.2064
9849.217 447.5249883.033433.21239922.871427.28089954.676426.39289986.481419.2468
9997.083419.016210018.33420.453110028.96424.363810060.83451.866710103.33 482.882
 10135.2499.768210156.45516.4259 10177.7518.370710188.33521.639710209.57535.0452
10301.16574.306610337.23596.802410379.96612.141610415.15631.465510446.92 644.851
#Mann= 3 , 0 , 0
 9542.86    0.12       0 9542.86    0.12       010446.92    0.12       0
#XS Ineff= 2 , 0
       0                               0
Bank Sta=9542.86,10446.92
Exp/Cntr=0.3,0.1

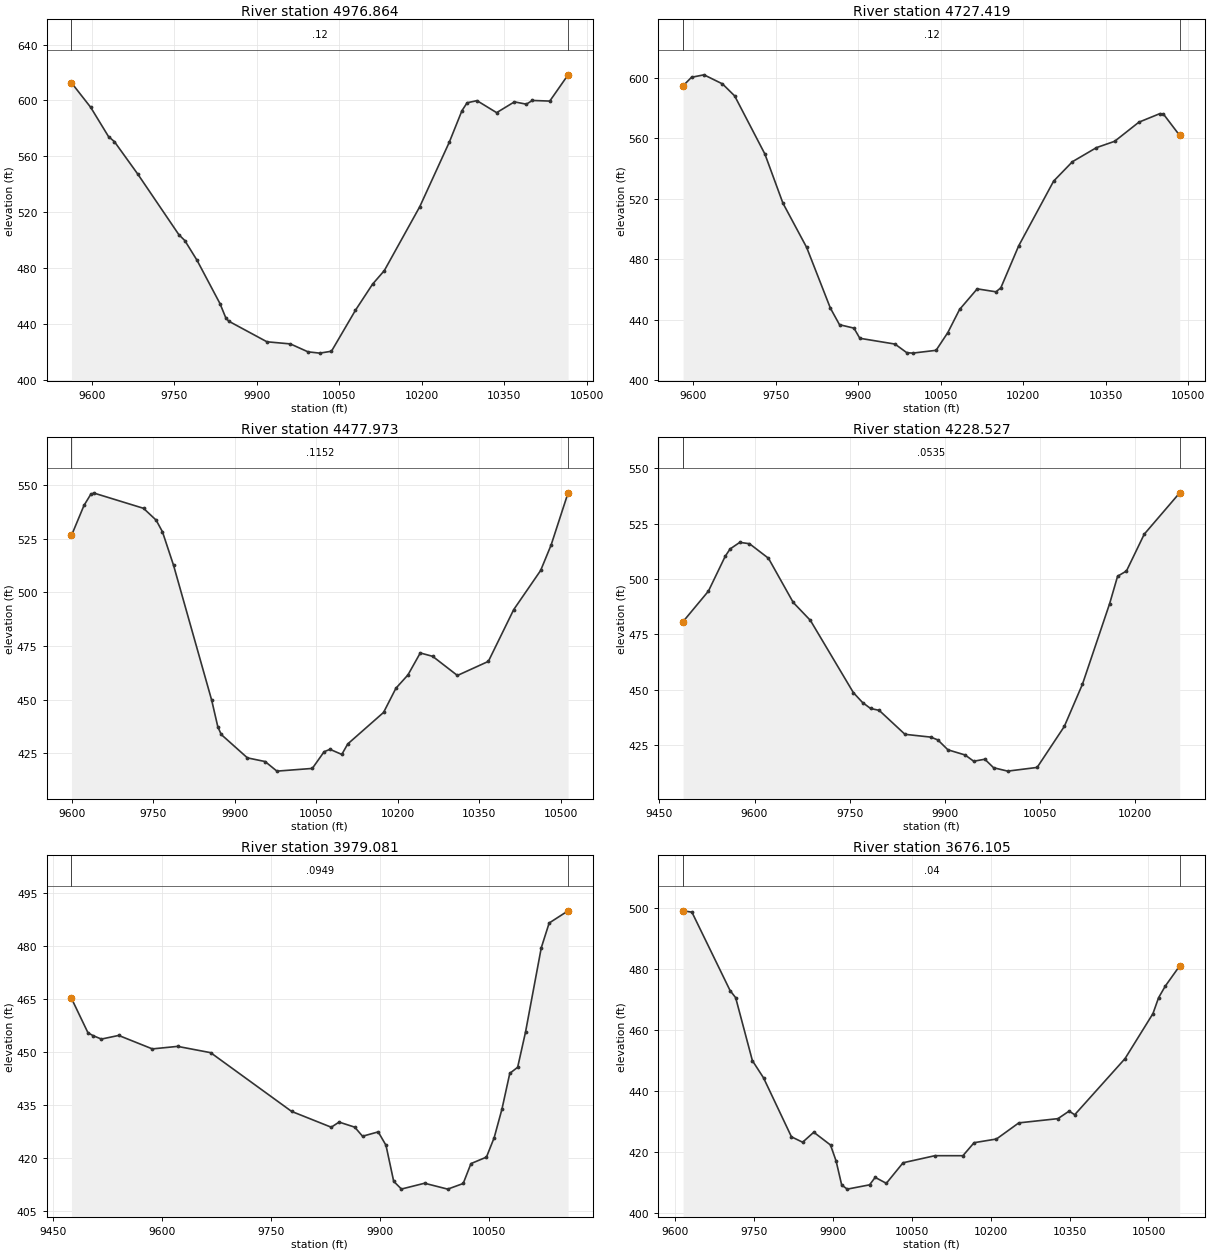
Type RM Length L Ch R = 1 ,4976.864,249.445700,249.445700,249.445700
XS GIS Cut Line= 6
 484332.71617549807853.591033461484400.218853102807881.116189752
484742.445089915808007.675288448484859.746624191808051.291932387
485079.611257007808137.762942233485174.889266906808177.921695945
#Sta/Elev= 30
9563.223612.62959598.088595.07759630.486 574.136 9641.22570.48949683.867547.1247
9758.501503.72779769.163499.61379791.467485.39479833.135454.38159843.797444.0848
9849.126441.7823 9918.43427.04249961.078425.51289993.064419.835910014.39418.9115
10035.73420.2596 10079.4449.679110110.42 468.33910131.79478.051510196.27523.8973
10249.99570.180710272.89592.653310282.23598.314410300.21599.853610335.96 591.248
10368.25598.986110389.96597.326210400.81599.996110432.53599.5403 10465.8618.3603
#Mann= 3 , 0 , 0
9563.223    0.12       09563.223    0.12       0 10465.8    0.12       0
#XS Ineff= 2 , 0
       0                               0
Bank Sta=9563.223,10465.8
Exp/Cntr=0.3,0.1

Type RM Length L Ch R = 1 ,4727.419,249.445800,249.445800,249.445800
XS GIS Cut Line= 6
484271.571150459808078.205411112484319.369970948808103.816159511
484444.530963252808160.841831985484872.086660272808325.619613835
484958.513108126808363.187473024485101.730535798808431.011360365
#Sta/Elev= 30
9581.897594.58089597.132600.17029619.822601.79629653.442595.8043  9675.6587.8642
9730.528549.47639763.278517.0451 9806.47487.75699849.513447.72399866.172436.7025
9892.466  434.449903.122427.72689967.058423.90579988.369418.24679999.025417.9234
10041.75419.778710063.12431.528710084.48446.783410116.53460.3926 10150.7458.4291
 10159.5461.097110191.89 488.79210255.46531.580310289.63544.401310333.32553.7012
10366.36557.871910410.42570.506110448.27576.111510454.88575.955910484.65561.7176
#Mann= 3 , 0 , 0
9581.897    0.12       09581.897    0.12       010484.65    0.12       0
#XS Ineff= 2 , 0
       0                               0
Bank Sta=9581.897,10484.65
Exp/Cntr=0.3,0.1

Type RM Length L Ch R = 1 ,4477.973,249.445700,249.445700,249.445700
XS GIS Cut Line= 6
484216.511957614808280.463670593484320.441894623808354.001512488
484378.716742246808388.640972522484447.922857849808423.823802819
484768.303581045808565.938608212485020.757673369808711.133695201
#Sta/Elev= 30
9599.043526.49329622.066540.4697  9634.5545.6329 9640.27546.22549731.697539.1245
9754.964533.60979766.597528.18329787.062512.55719857.326449.71549868.544437.4196
9874.815433.83479923.023422.9524 9955.65421.23999977.401416.777510042.59418.0357
10064.31425.803510075.17426.929810096.89424.549410107.87429.435110173.87444.1126
10196.55455.351610218.72461.559210241.42471.791110264.23470.220110309.83461.3072
10366.84467.862910413.52  491.9610463.12510.1814 10482.5522.098210513.68546.3335
#Mann= 3 , 0 , 0
9599.043  0.1152       09599.043  0.1152       010513.68  0.1152       0
#XS Ineff= 2 , 0
       0                               0
Bank Sta=9599.043,10513.68
Exp/Cntr=0.3,0.1

Type RM Length L Ch R = 1 ,4228.527,249.445700,249.445700,249.445700
XS GIS Cut Line= 6
484106.584665641 808314.84012682484180.110393752808399.847924927
484424.448857655 808667.38943512484478.989459171808718.283965967
484603.233512847808845.118283796484642.823865652808884.363398588
#Sta/Elev= 30
9487.473480.80859527.349494.53649553.792510.25229561.482513.56929576.768  516.54
9592.054515.93789621.946509.37569661.015489.4156  9688.1481.29679755.814448.6976
9770.234444.2477  9782.9441.54999796.443440.71239837.071429.89429877.699428.6298
9888.865427.37219904.785422.9004 9931.87420.56379945.413417.74689962.954418.6444
9976.786414.8023    9999413.274410045.39 414.94310088.19 433.43610116.84452.5351
10159.71 488.94310172.19501.252310186.18503.625310214.18520.233310270.09538.9076
#Mann= 3 , 0 , 0
9487.473  0.0535       09487.473  0.0535       010270.09  0.0535       0
#XS Ineff= 2 , 0
       0                               0
Bank Sta=9487.473,10270.09
Exp/Cntr=0.3,0.1

Type RM Length L Ch R = 1 ,3979.081,302.976700,302.976700,302.976700
XS GIS Cut Line= 6
484002.648477439808329.883522477484085.035065349808467.243412482
484126.714217251808547.278005109484162.712296108808625.837991607
484253.701821783808867.883876545484288.425373522808948.671350527
#Sta/Elev= 30
9475.935 465.1959498.637455.43179505.869454.60579517.095453.65629540.899  454.69
 9587.22450.86859621.962451.58469667.435449.7981 9778.87433.13749833.426428.6517
9844.194430.10749865.731428.67069876.499426.09199898.035427.3262 9908.73 423.536
9919.352413.30979929.973411.11129961.838412.75889993.702411.0884   10015412.6861
10025.67418.3268   10047420.170410057.66425.696810068.33433.783910079.12443.9348
10089.95445.656510100.79455.654310122.45 479.54910133.29486.579710159.35490.0394
#Mann= 3 , 0 , 0
9475.935  0.0949       09475.935  0.0949       010159.35  0.0949       0
#XS Ineff= 2 , 0
       0                               0
Bank Sta=9475.935,10159.35
Exp/Cntr=0.3,0.1

Type RM Length L Ch R = 1 ,3676.105,694.806300,694.806300,694.806300
XS GIS Cut Line= 3
483809.411390096808520.890104741483966.515378445808963.637708351
484412.833527237809124.312241927
#Sta/Elev= 30
9615.244499.14269631.956498.70739704.492 473.0049715.103470.66699746.935450.0104
9768.157 444.3589821.212425.02899842.433423.25639863.655426.53499895.488422.3368
9906.099417.0955 9916.71 409.2299927.321407.87299969.764409.28169980.375411.7261
 10001.6 409.78110033.43416.518810094.06418.8409 10147.2 418.83510168.45423.1004
10210.97424.308610253.48429.599510327.88430.987710349.13433.458510359.76432.2686
10455.42450.673910508.56 465.44910519.19470.6376 10531.9474.4343 10559.4481.0972
#Mann= 3 , 0 , 0
9615.244    0.04       09615.244    0.04       0 10559.4    0.04       0
#XS Ineff= 2 , 0
       0                               0
Bank Sta=9615.244,10559.4
Exp/Cntr=0.3,0.1