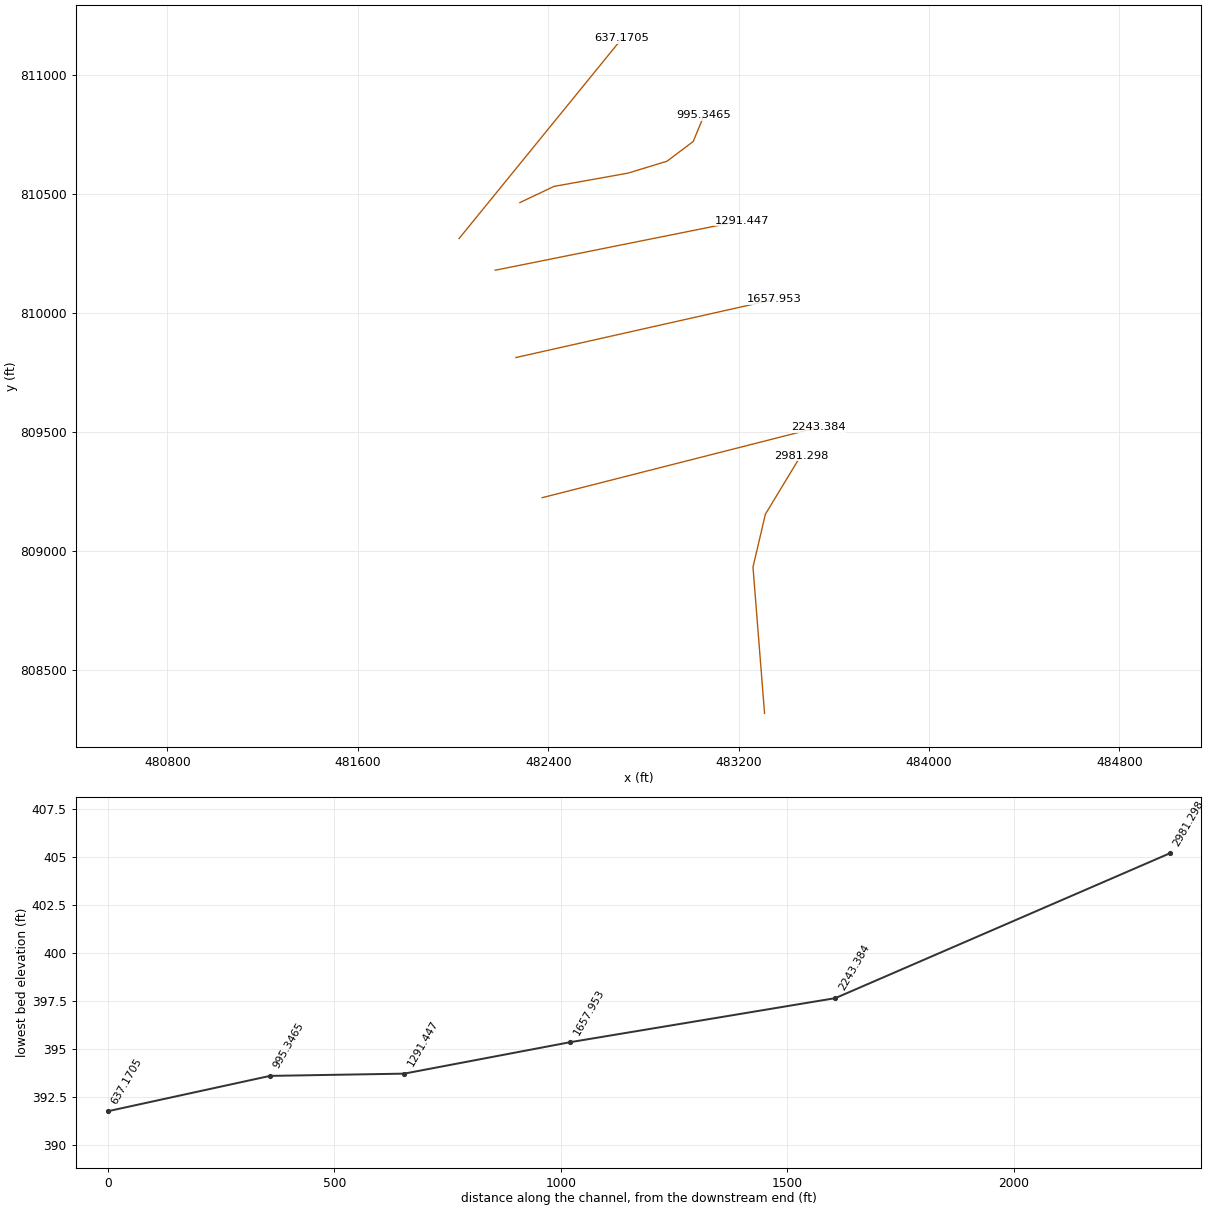
HEC-RAS study 5528_ras.prj: 5528

--- 5528_ras.g01 (geometry) --- (continued)

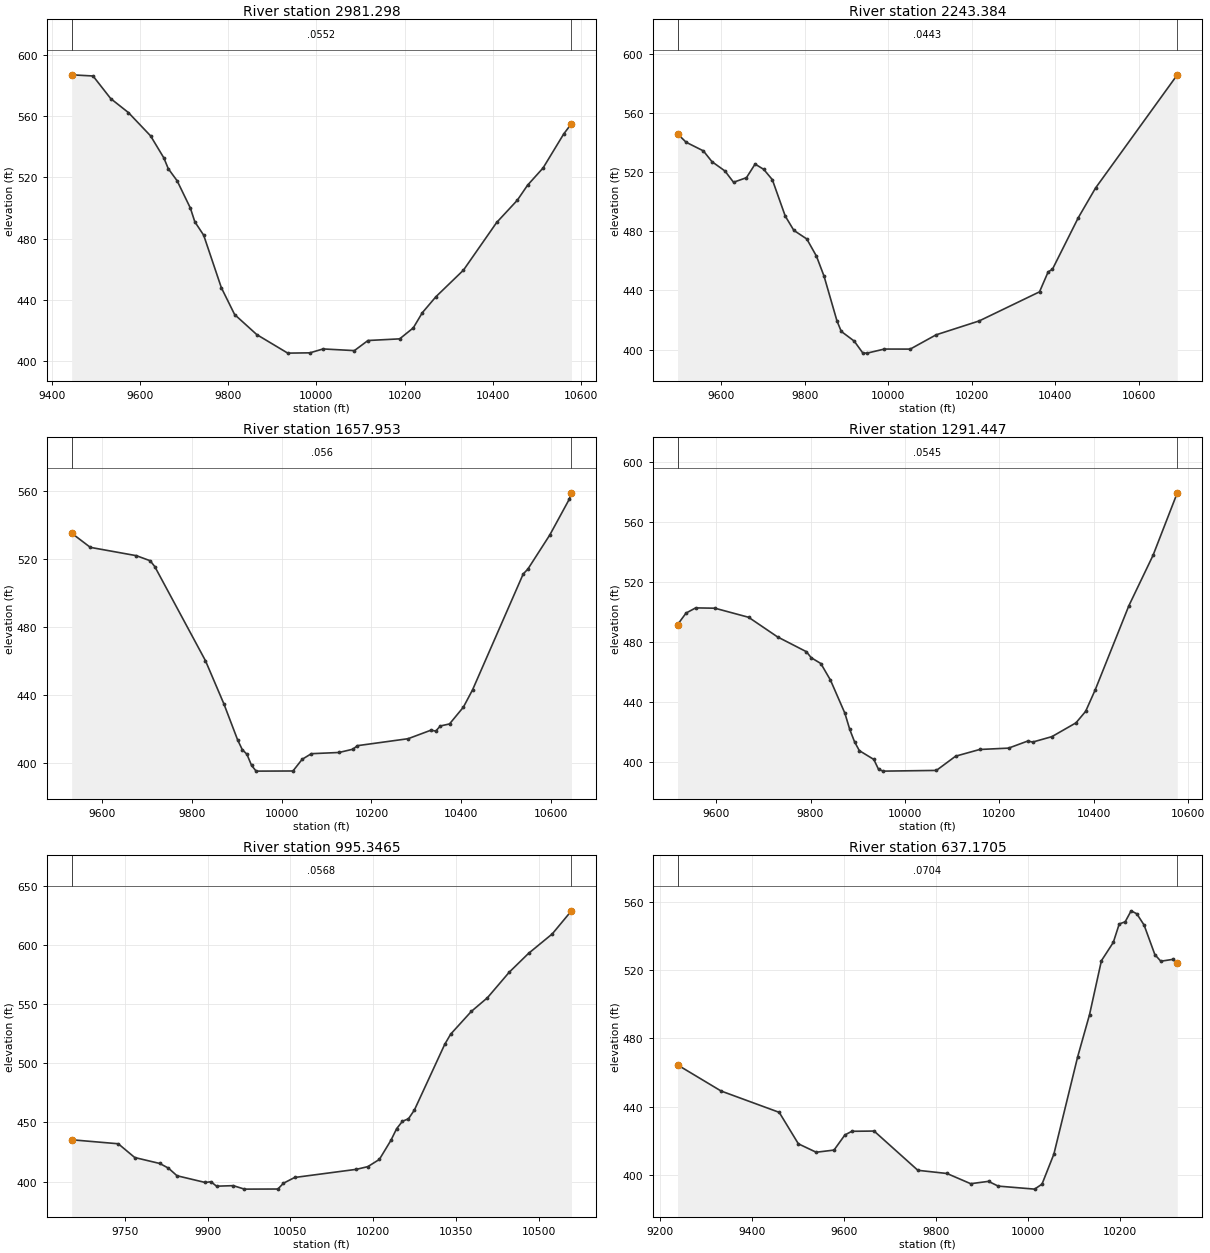
Type RM Length L Ch R = 1 ,2981.298,737.914800,737.914800,737.914800
XS GIS Cut Line= 4
483309.015656203808316.677050576483260.404545099808931.260383904
483312.487878412809153.482606143483461.793433994809400.010383919
#Sta/Elev= 30
9445.285586.84599493.759  586.099533.884571.30679574.009562.19199624.165547.0155
9654.259 532.621 9664.29525.58599684.352517.69899714.446499.83739724.477490.9115
 9744.54 482.1659784.665447.86519814.758430.35579864.915417.28839935.133405.1829
9985.289405.374610015.38407.917710086.17406.823310116.98413.417810188.88414.5026
10219.69421.658710240.24431.583610271.05442.012510333.49459.378410408.72490.4689
10455.48504.981110478.86 514.84410513.93526.0518 10560.7548.240210578.25554.9637
#Mann= 3 , 0 , 0
9445.285  0.0552       09445.285  0.0552       010578.25  0.0552       0
#XS Ineff= 2 , 0
       0                               0
Bank Sta=9445.285,10578.25
Exp/Cntr=0.3,0.1

Type RM Length L Ch R = 1 ,2243.384,585.430800,585.430800,585.430800
XS GIS Cut Line= 2
482374.987878412809222.927050591483534.710100651809518.065939456
#Sta/Elev= 30
9495.458545.77729516.108540.09479557.383 534.263 9578.02526.96069608.977520.6977
9629.614513.0478 9660.57516.15279681.208525.33199701.845521.78519722.483514.8332
9753.439490.21449774.077480.53979805.033474.75729828.236463.09599846.308449.6554
9877.264419.43119887.583412.30779918.539405.77599939.177397.72449949.495 397.637
 9990.77400.387610052.68400.3556 10114.6409.997410217.78419.382910362.25439.0419
10382.88452.4999 10393.2 454.29710455.11489.133610496.39509.161710692.15585.6294
#Mann= 3 , 0 , 0
9495.458  0.0443       09495.458  0.0443       010692.15  0.0443       0
#XS Ineff= 2 , 0
       0                               0
Bank Sta=9495.458,10692.15
Exp/Cntr=0.3,0.1

Type RM Length L Ch R = 1 ,1657.953,366.505800,366.505800,366.505800
XS GIS Cut Line= 2
482264.446606934809811.662462711483349.752594829810055.573656335
#Sta/Elev= 30
9532.664535.43629574.229527.08589676.723522.18879707.471 519.2019717.721515.7422
9830.465460.36759871.462434.95499902.211413.6212 9912.46407.97889922.709405.2942
9932.959398.76549943.208395.3404 10025.2395.4247 10045.7402.3082 10066.2405.6073
 10127.7406.322710158.45408.2334 10168.7 410.32810281.44414.424210332.69419.4818
10342.94418.912310353.19421.919610373.68423.124410404.43432.978610424.93443.2021
10537.68511.438210547.92514.256210596.82534.378610640.17 555.43510645.04559.1943
#Mann= 3 , 0 , 0
9532.664   0.056       09532.664   0.056       010645.04   0.056       0
#XS Ineff= 2 , 0
       0                               0
Bank Sta=9532.664,10645.04
Exp/Cntr=0.3,0.1

Type RM Length L Ch R = 1 ,1291.447,296.100500,296.100500,296.100500
XS GIS Cut Line= 2
482177.261158273810178.502360567483215.455602721810386.835693895
#Sta/Elev= 30
9518.125491.55949536.217499.34789556.616502.80969597.413502.59719668.809496.5272
9730.005483.43229791.201473.5227  9801.4469.51469821.799465.62419842.198454.5395
9872.796 432.3789882.995421.63519893.195413.32939903.394407.38999933.992401.5268
9944.191394.82889954.391   393.710066.58394.174710107.38403.691810158.38408.1681
10219.57409.077910260.37413.830210270.57413.114310311.37416.755310362.36425.9772
10382.76433.627410403.16448.068710474.56504.372510525.55537.898410577.02579.7192
#Mann= 3 , 0 , 0
9518.125  0.0545       09518.125  0.0545       010577.02  0.0545       0
#XS Ineff= 2 , 0
       0                               0
Bank Sta=9518.125,10577.02
Exp/Cntr=0.3,0.1

Type RM Length L Ch R = 1 ,995.3465,358.176000,358.176000,358.176000
XS GIS Cut Line= 6
482281.130367528810462.667156828482424.459706812  810530.6678373
482734.591984391810586.250004913482899.432147822810636.511828839
483009.458502164810719.587724879483054.546035906810828.696193152
#Sta/Elev= 30
9653.688435.30589738.137431.92259767.956420.29739813.366415.25139829.111411.3015
9844.484404.90069895.761399.18619905.971399.8476 9916.14396.07439946.464396.5151
 9966.68393.583110027.29 393.67210037.39398.575710057.59403.425610169.62410.3264
10190.19412.598910211.08418.691910231.97434.779310242.41444.691810252.98450.9678
10263.76453.010610274.53 460.41410329.52515.973110340.25524.576510377.61543.7652
10406.82555.335110446.37576.952410481.42592.893610524.27 609.30510559.07628.8281
#Mann= 3 , 0 , 0
9653.688  0.0568       09653.688  0.0568       010559.07  0.0568       0
#XS Ineff= 2 , 0
       09733.929                       0
Bank Sta=9653.688,10559.07
Exp/Cntr=0.3,0.1

Type RM Length L Ch R = 1 ,637.1705,0.000000,0.000000,0.000000
XS GIS Cut Line= 2
482025.605692089810311.574278966482710.501525372811152.720112309
#Sta/Elev= 30
9238.997464.47929333.685 449.1659459.766436.68589501.329418.26269540.016413.3347
9578.703414.60479602.305423.4648 9617.39425.59629665.655425.74139760.681402.7572
9823.721400.90069875.304394.91999913.991396.28889934.896393.514710014.08391.7403
10030.05394.663410055.84 412.23610107.43 469.15510133.22493.884610159.01525.4581
 10184.8536.1865 10197.7546.972910210.59548.243310223.49554.665310235.81552.9309
10251.65546.325310275.07529.003310287.97525.165810313.76526.231310323.71523.9736
#Mann= 3 , 0 , 0
9238.997  0.0704       09238.997  0.0704       010323.71  0.0704       0
#XS Ineff= 2 , 0
       09668.579                       0
Bank Sta=9238.997,10323.71
Exp/Cntr=0.3,0.1